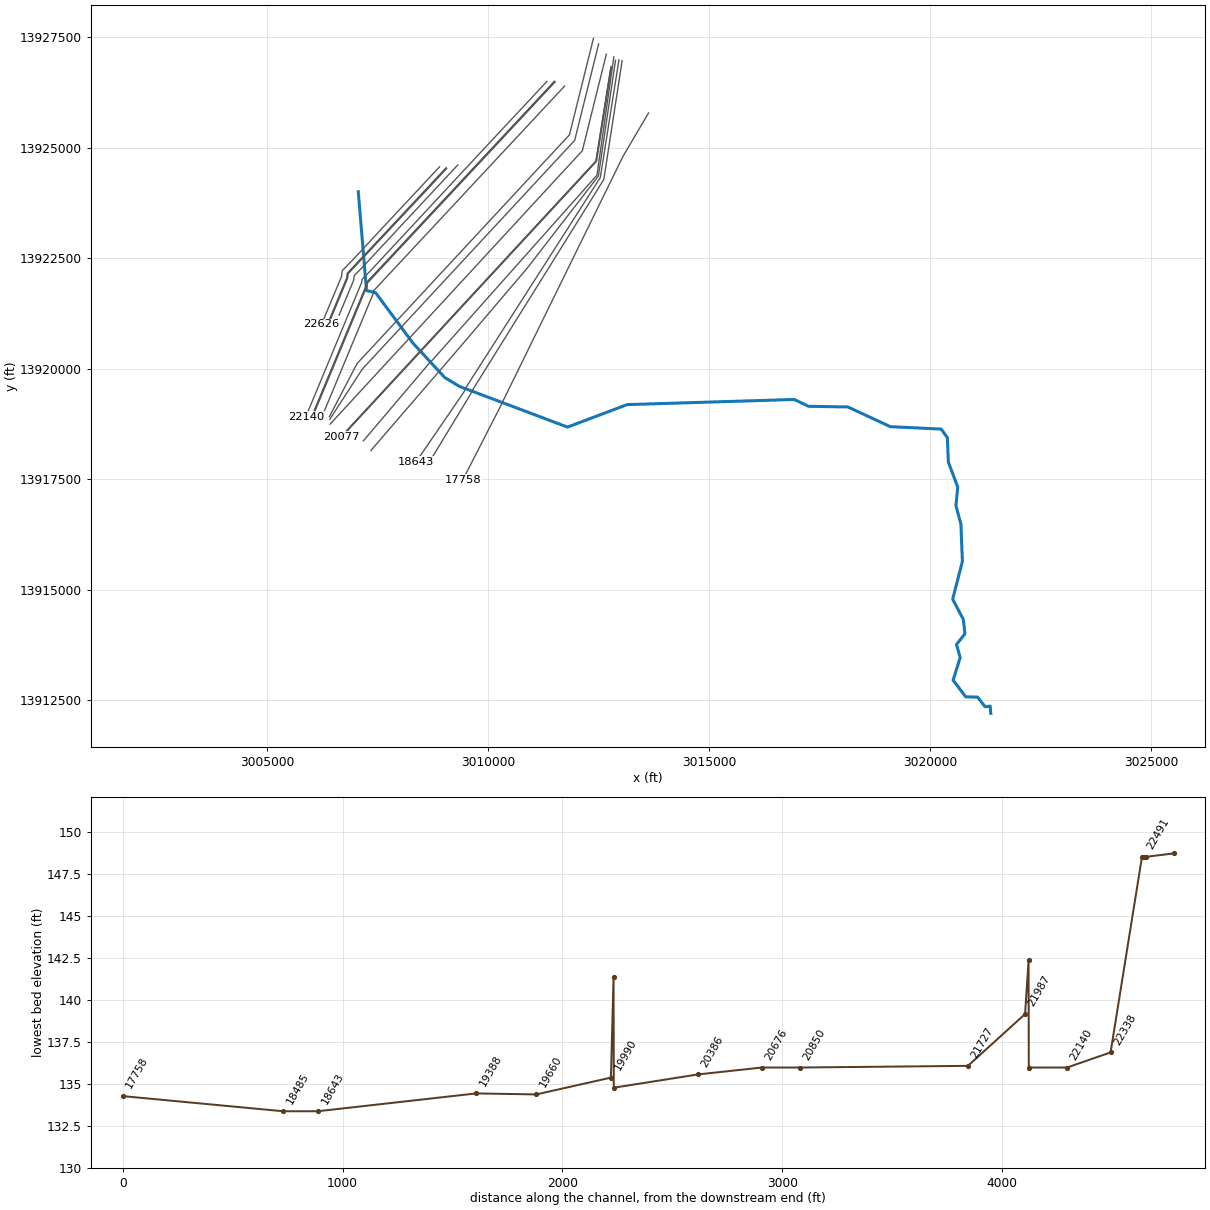
--- k145-00-00.prj (project) ---

Proj Title=K145-00-00
Current Plan=p02
Default Exp/Contr=.3,.1
English Units
Geom File=g01
Flow File=f01
Flow File=f02
Plan File=p01
Plan File=p02
Y Axis Title=Elevation
X Axis Title(PF)=Main Channel Distance
X Axis Title(XS)=Station
BEGIN DESCRIPTION:
HCFCD MODEL SUMMARY METADATA
The purpose of this summary is to document the high points of hydrologic and hydraulic models filed within the HCFCD Model and Map Management (M3) system.  The document includes references to the project that prompted the creation or update of the model.
DESCRIPTION OF PROJECT:
The following model was the hydraulic model which represented the effective condition of Harris County's watersheds.
PURPOSE OF PROJECT:
Development of effective models to support the National Flood Insurance Program.
HCFCD Watershed Unit ID: K
M3 Study Identifier: 2007_Effective_K
Engineer: HCFCD
Project Name: EffectiveFEMA Study for watershed Cypress Creek (K)
Study Completion Date: 6/18/2007
FEMA Case Number: [No Data]
FEMA Approval Date: [No Date in Database]
Vertical Datum: NAVD 1988
Datum Note: 2001 ADJ
HYDRAULICS
HCFCD Unit No.:  K145-00-00
Hydraulic Program Name: HEC-RAS
Hydraulic Program Version: 3.0.1
Steady Hydraulic Model: Yes
Unsteady Hydraulic Model: No
Update1:
The effective FEMA hydraulic model for unit number K145-00-00 has been updated by FEMA LOMR 10-06-0650P with an effective date of 5/27/2010.
Update2:
The effective FEMA hydraulic model for unit number K145-00-00 has been updated by FEMA LOMR 10-06-2260P with an effective date of 1/7/2011.
Update3:
The effective FEMA hydraulic model for unit number K145-00-00 has been updated by FEMA LOMR 15-06-3864P with an effective date of 11/18/2016.
END DESCRIPTION:
DSS Export Rating Curves= 0
DSS Export Rating Curve Sorted= 0
DSS Export Volume Flow Curves= 0
DXF OffsetX= 0
DXF OffsetY= 0
DXF ScaleX= 1
DXF ScaleY= 10

--- k145-00-00.p02 (plan) ---

Plan Title=FEMA Effective Floodway
Version=Version 3.0.1  May 2012
Short Identifier=EFF+LOMR FW
Geom File=g01
Flow File=f02
Subcritical Flow
K Sum by GR= 0
Std Step Tol= 0.01
Critical Tol= 0.01
Num of Std Step Trials= 20
Max Error Tol= 0.3
Flow Tol Ratio= 0.001
Split Flow NTrial= 30
Split Flow Tol= 0.02
Split Flow Ratio= 0.02
Log Output Level= 0
Friction Slope Method= 1
Unsteady Friction Slope Method= 2
Parabolic Critical Depth
Global Vel Dist= 0 , 0 , 0
Global Log Level= 0
CheckData=True
Encroach Param=-1 ,0,0, 2
Encroach River=K145-00-00
Encroach Reach=K145-00-00_0012
Encroach Node=22626
       1    4900    5010
Encroach Node=22501
       1    4900    5010
Encroach Node=22491
       1    4900    5010
Encroach Node=22481
       1    4900    5010
Encroach Node=22410
       1    4926    5114
Encroach Node=22338
       1    4926    5114
Encroach Node=22140
       1    4820    5215
Encroach Node=22004
       1    4889    5162
Encroach Node=22003
       1    4889    5266
Encroach Node=21987
       1    4885    5112
Encroach Node=21857
       1    4819    5425
Encroach Node=21727
       1    4819    5425
Encroach Node=20850
       1    4798    5106
Encroach Node=20676
       1    4898    5100
Encroach Node=20386
       1    4880    5392
Encroach Node=20077
       1    4892    5163
Encroach Node=20076
       1    4892    5087
Encroach Node=19990
       1    4889    5076
Encroach Node=19820
       1    4856    5403
Encroach Node=19660
       1    4856    5403
Encroach Node=19388
       1    4841    5151
Encroach Node=18643
       1    4847    5157
Encroach Node=18485
       1    4849    5155
Encroach Node=17758
       1    4843    5149
Encroach Node=17693
       1    4845    5151
Encroach Node=17581
       1    4843    5154
Encroach Node=17504
       1    4848    5152
Encroach Node=17503
       1    4848    5152
Encroach Node=17484
       1  4942.6  5058.2
Encroach Node=17456
       1  4942.6  5058.2
Encroach Node=17429
       1  4942.6  5058.2
Encroach Node=17419
       1  4942.6  5058.2
Encroach Node=17306
       1  4942.6  5058.2
Encroach Node=17206
       1  4925.5  5071.8
Encroach Node=16594
       1  4940.6  5075.6
Encroach Node=16434
       1  4938.6  5073.6
Encroach Node=16004
       1  4933.9  5068.9
Encroach Node=15254
       1    4934    5069
Encroach Node=15094
       1    4932  5079.6
Encroach Node=15084
       1    4932  5079.6
Encroach Node=15074
       1    4932  5079.6
Encroach Node=14974
       1  4930.6    5056
Encroach Node=14675
       1  4930.9  5058.9
Encroach Node=14575
       1 4944.37 5052.07
Encroach Node=14565
       1 4944.37 5052.07
Encroach Node=14560
       1  4952.2  5060.6
Encroach Node=14555
       1  4952.2  5060.6
Encroach Node=14455
       1  4952.2  5060.6
Encroach Node=14384
       1 4943.56  5058.1
Encroach Node=13343
       1  4934.8  5066.4
Encroach Node=12617
       1  4942.8  5058.9
Encroach Node=10826
       1  4939.8  5057.4
Encroach Node=10726
       1  4955.9  5025.4
Encroach Node=10716
       1  4955.9  5025.4
Encroach Node=10657
       1  4955.9  5025.4
Encroach Node=10557
       1  4935.7  5053.6
Encroach Node=9923
       1  4938.3  5055.3
Encroach Node=9823
       1  4941.8  5060.6
Encroach Node=9813
       1  4941.8  5060.6
Encroach Node=9778
       1  4941.8  5060.6
Encroach Node=9678
       1  4938.1 5060.22
Encroach Node=8154
       1  4941.2  5054.4
Encroach Node=6310
       1    4830    5108
Encroach Node=6210
       1    4833    5097
Encroach Node=6200
       1    4790    5150
Encroach Node=6149
       1    4845    5096
Encroach Node=6049
       1    4856 5082.89
Encroach Node=4638
       1 4892.85 5112.85
Encroach Node=4453
       1  4972.7  5121.3
Encroach Node=3111
       1    4900    5180
Encroach Node=2068
       1    4800    5200
Encroach Node=2032
       1    4760    5245
Encroach Node=2030
       1    4755    5255
Encroach Node=2022
       1    4750    5260
Encroach Node=1984
       1    4735    5260
Encroach Node=1958
       1    4735    5260
Encroach Node=1896
       1    4735    5300
Encroach Node=1812
       1    4900    5400
Encroach Node=1169
       1    4870  5449.9
Encroach Node=1108
       1    4800  5440.6
Encroach Node=1072
       1    4800  5411.2
BEGIN DESCRIPTION:
FEMA Effective Floodway June 2007 + LOMR 10-06-0650P + LOMR 10-06-2260P + LOMR 15-06-3864P November 2016
END DESCRIPTION:
Computation Interval=1HOUR
Output Interval=1HOUR
Run HTab= 0
Run UNet= 0
Run PostProcess= 0
UNET Theta= 1
UNET ZTol= 0.02
UNET ZSATol= 0.1
UNET MxIter= 20
UNET MaxInSteps= 20
UNET DtIC= 0
UNET DtMin= 0
UNET MaxCRTS= 20
UNET WFStab= 2
UNET SFStab= 1
UNET WFX= 1
UNET SFX= 1
UNET Convert EG Bridges=-1
UNET Use Existing IB Tables=-1
Instantaneous Interval=1HOUR
Write IC File= 0
Write Velocity= 0
Write Detailed= 0

--- k145-00-00.p01 (plan) ---

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Plan Title=FEMA Effective Multi-Profile
Short Identifier=EFF+LOMR MP
Geom File=g01
Flow File=f01
Encroach Param=-1 ,0,0, 0
FEMA Effective Multi-Profile June 2007 + LOMR 10-06-0650P + LOMR 10-06-2260P + LOMR 15-06-3864P November 2016

--- k145-00-00.f02 (steady flow) ---

Flow Title=FEMA Effecitve Floodway
Version=Version 3.0.1  May 2012
Number of Profiles= 2
Profile Names=1PCT_100yr, 1PCTFloodway_100yrFW
River Rch & RM=K145-00-00,K145-00-00_0012 ,22626
     491     491
River Rch & RM=K145-00-00,K145-00-00_0012 ,21727
     672     672
River Rch & RM=K145-00-00,K145-00-00_0012 ,19660
     672     672
River Rch & RM=K145-00-00,K145-00-00_0012 ,16004
    1700    1700
River Rch & RM=K145-00-00,K145-00-00_0012 ,14560
    1810    1810
River Rch & RM=K145-00-00,K145-00-00_0012 ,13343
    1880    1880
River Rch & RM=K145-00-00,K145-00-00_0012 ,12617
    2100    2100
River Rch & RM=K145-00-00,K145-00-00_0012 ,10726
    2200    2200
River Rch & RM=K145-00-00,K145-00-00_0012 ,9823
    2460    2460
River Rch & RM=K145-00-00,K145-00-00_0012 ,6210
    2600    2600
River Rch & RM=K145-00-00,K145-00-00_0012 ,4453
    2680    2680
River Rch & RM=K145-00-00,K145-00-00_0012 ,1984
  2753.1  2753.1
Boundary for River Rch & Prof#=K145-00-00,K145-00-00_0012 , 1
Up Type= 0
Dn Type= 3
Dn Slope=.0009
Boundary for River Rch & Prof#=K145-00-00,K145-00-00_0012 , 2
Up Type= 0
Dn Type= 1
Dn Known WS=137.68
DSS Import GetInterval= 0
DSS Import GetPeak= 0
DSS Import FillOption= 0

--- k145-00-00.f01 (steady flow) ---

Flow Title=FEMA Effective Multi-Profile
Version=Version 3.0.1  Mar 2001
Number of Profiles= 4
Profile Names=10PCT_10yr, 2PCT_50yr, 1PCT_100yr, 0.2PCT_500yr
River Rch & RM=K145-00-00,K145-00-00_0012 ,22626
     164     403     491     783
River Rch & RM=K145-00-00,K145-00-00_0012 ,21727
     155     478     672    1123
River Rch & RM=K145-00-00,K145-00-00_0012 ,19660
     155     478     672    1123
River Rch & RM=K145-00-00,K145-00-00_0012 ,16004
     840    1500    1700    2500
River Rch & RM=K145-00-00,K145-00-00_0012 ,14560
     900    1590    1810    2690
River Rch & RM=K145-00-00,K145-00-00_0012 ,13343
     930    1650    1880    2820
River Rch & RM=K145-00-00,K145-00-00_0012 ,12617
    1050    1820    2100    3220
River Rch & RM=K145-00-00,K145-00-00_0012 ,10726
    1100    1900    2200    3400
River Rch & RM=K145-00-00,K145-00-00_0012 ,9823
    1230    2030    2460    3790
River Rch & RM=K145-00-00,K145-00-00_0012 ,6210
    1300    2100    2600    4000
River Rch & RM=K145-00-00,K145-00-00_0012 ,4453
    1360    2200    2680    4080
River Rch & RM=K145-00-00,K145-00-00_0012 ,1984
  1405.7  2281.3  2753.1  4143.1
Boundary for River Rch & Prof#=K145-00-00,K145-00-00_0012 , 1
Up Type= 0
Dn Type= 3
Dn Slope=.0009
Boundary for River Rch & Prof#=K145-00-00,K145-00-00_0012 , 2
Up Type= 0
Dn Type= 3
Dn Slope=.0009
Boundary for River Rch & Prof#=K145-00-00,K145-00-00_0012 , 3
Up Type= 0
Dn Type= 3
Dn Slope=.0009
Boundary for River Rch & Prof#=K145-00-00,K145-00-00_0012 , 4
Up Type= 0
Dn Type= 3
Dn Slope=.0009
DSS Import GetInterval= 0
DSS Import GetPeak= 0
DSS Import FillOption= 0

--- k145-00-00.g01 (geometry) ---

Geom Title=K145-00-00 2016
Version=Version 3.0.1  May 2012

River Reach=K145-00-00      ,K145-00-00_0012
Reach XY= 30
      3007058.34     13924004.75      3007244.15     13921770.85
      3007450.27     13921722.31      3008294.93     13920582.27
      3009012.87     13919804.54       3009343.6     13919604.02
      3011790.65     13918682.15      3013139.61     13919190.83
      3016919.12     13919307.15       3017244.3     13919152.53
      3018132.66     13919137.88      3019095.34      13918691.7
      3020245.23     13918636.89      3020383.62     13918441.67
      3020406.97     13917888.75      3020618.78     13917327.11
      3020577.98     13916905.24      3020690.82     13916484.23
      3020723.81     13915643.09      3020504.19     13914790.66
      3020744.37     13914332.13      3020781.48     13914006.37
       3020589.8      13913764.8      3020673.63     13913468.06
       3020514.4     13912958.54      3020798.55      13912579.5
      3021066.91      13912574.8      3021238.16     13912355.33
      3021353.61     13912370.09      3021365.18      13912206.3

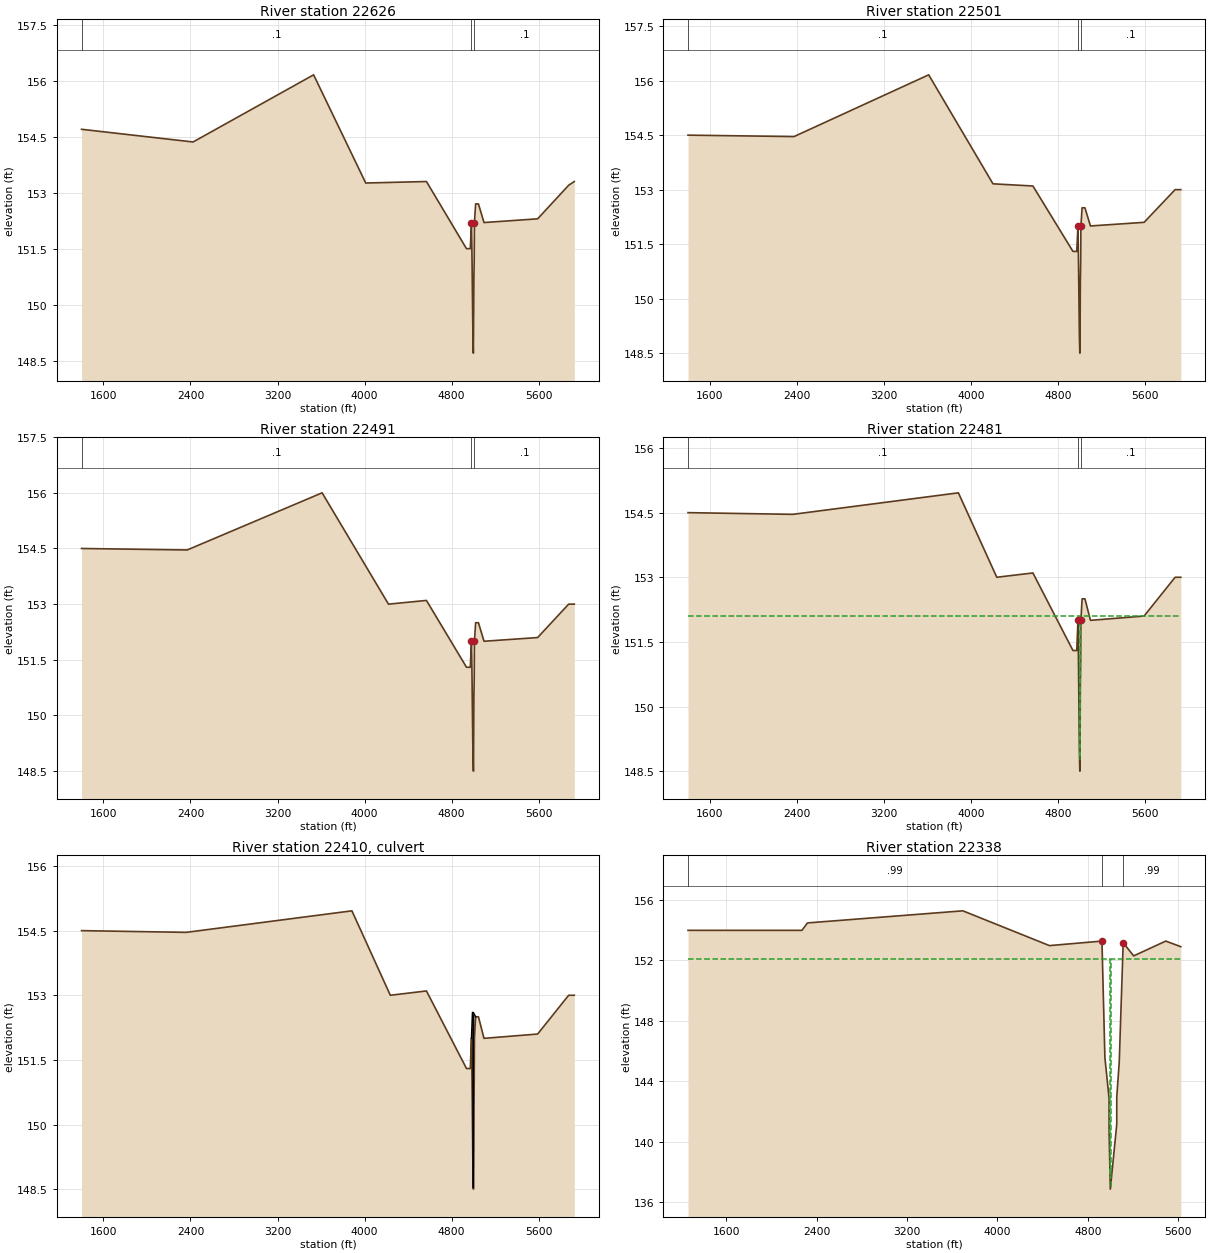
Type RM Length L Ch R = 1 ,22626   ,125,125,125
BEGIN DESCRIPTION:
END OF IMPROVEMENTS
END DESCRIPTION:
XS GIS Cut Line= 6
      3008897.32     13924570.68      3007661.71     13923248.96
      3006951.82     13922482.93      3006695.88     13922221.98
      3006678.01     13922086.29      3006227.25     13921004.48
#Sta/Elev= 22
    1399   154.7    2424  154.36    3532  156.16    4011  153.26    4569   153.3
    4937   151.5    4972   151.5    4983   152.2    4988   151.2    4992   150.2
    4996   149.2    5000   148.7    5004   150.2    5005   150.7    5008   151.2
    5010   152.2    5021   152.7    5047   152.7    5098   152.2    5591   152.3
    5876   153.2    5928   153.3
#Mann= 3 ,-1 , 0
    1399      .1       0    4983     .08       0    5010      .1       0
#Block Obstruct= 2 , 0
         1137.25  154.35
Bank Sta=4983,5010
XS Rating Curve= 0
Exp/Cntr=.3,.1

Type RM Length L Ch R = 1 ,22501   ,10,10,10
XS GIS Cut Line= 6
      3009042.09     13924546.12      3007747.81     13923161.01
      3006810.14     13922162.68      3006795.69     13922052.94
      3006705.58     13921836.68      3006349.51     13920982.13
#Sta/Elev= 23
    1399   154.5    2373  154.46    3611  156.16    4202  153.16    4569   153.1
    4937   151.3    4972   151.3    4983     152    4988     151    4992     150
    4996     149    5000   148.5  5001.5   148.5    5004     150    5005   150.5
    5008     151    5010     152    5021   152.5    5047   152.5    5098     152
    5591   152.1    5876     153    5928     153
#Mann= 3 ,-1 , 0
    1399      .1       0    4983     .08       0    5010      .1       0
#Block Obstruct= 2 , 0
         1137.25  154.15
Bank Sta=4983,5010
XS Rating Curve= 0
Exp/Cntr=.8,.6

Type RM Length L Ch R = 1 ,22491   ,10,10,10
XS GIS Cut Line= 6
      3009049.43     13924539.33      3007755.12     13923154.19
      3006819.62     13922158.06      3006805.43     13922050.32
      3006715.27     13921833.94      3006358.34     13920977.32
#Sta/Elev= 23
    1399   154.5    2370  154.46    3610     156    4220     153    4569   153.1
    4937   151.3    4972   151.3    4983     152    4988     151    4992     150
    4996     149    5000   148.5  5001.5   148.5    5004     150    5005   150.5
    5008     151    5010     152    5021   152.5    5047   152.5    5098     152
    5591   152.1    5876     153    5928     153
#Mann= 3 ,-1 , 0
    1399      .1       0    4983     .08       0    5010      .1       0
#Block Obstruct= 2 , 0
         1137.25  154.15
Bank Sta=4983,5010
XS Rating Curve= 0
Exp/Cntr=.8,.6

Type RM Length L Ch R = 1 ,22481   ,143,143,143
XS GIS Cut Line= 6
      3009056.77     13924532.53      3008621.64     13924062.35
       3006829.1     13922153.45      3006815.18      13922047.7
      3006724.96     13921831.19      3006367.29      13920972.8
#Sta/Elev= 23
    1399   154.5    2361  154.46    3884  154.96    4237     153    4569   153.1
    4937   151.3    4972   151.3    4983     152    4988     151    4992     150
    4996     149    5000   148.5  5001.5   148.5    5004     150    5005   150.5
    5008     151    5010     152    5021   152.5    5047   152.5    5098     152
    5591   152.1    5876     153    5928     153
#Mann= 3 ,-1 , 0
    1399      .1       0    4983     .08       0    5010      .1       0
#XS Ineff= 2 , 0
       0    4998   152.1    5002       0   152.1
Permanent Ineff=
       F       F
#Block Obstruct= 2 , 0
         1137.25  154.15
Bank Sta=4983,5010
XS Rating Curve= 0
Exp/Cntr=.8,.6

Type RM Length L Ch R = 2 ,22410   ,,,
Bridge Culvert--1,0,-1,-1, 0
Deck Dist Width WeirC Skew NumUp NumDn MinLoCord MaxHiCord MaxSubmerge Is_Ogee
1,120,2.6,0, 4, 2, , , .95, 0, 0,0,,
    4983    4992    5000    5021
     152   152.6   152.6   152.5
   148.4   148.4   148.4   148.4
    4926    5114
  153.25  153.15
  136.85  136.85
BR Coef=-1 , 0 , 0 ,, 0 ,,,.8,-1,,0,
WSPro=,,,, 1 ,,,, 0 ,,,, 0 ,,,,-1 ,-1 ,-1 , 0 , 0 , 0 , 0 , 0
Culvert=1,4,,140,.013,1,1,1,3,148.53,5000,137.03,5000,Culvert #1  , 0 ,1
Culvert Bottom n=.013
BC Design=,, 0 ,, 0 ,,,,,,
BC HTab HWMax=154.96

Type RM Length L Ch R = 1 ,22338   ,221,198,204
XS GIS Cut Line= 6
      3009309.47     13924611.93      3007901.02     13923103.46
      3007190.03     13922336.23      3006967.68     13922109.54
      3006953.76     13922003.79      3006625.51     13921216.57
#Sta/Elev= 17
    1260  153.97    2269  153.97    2318  154.46    3694  155.26    4461  152.96
    4926  153.26    4952  145.56    4989  142.86    4989  140.76    5000  136.86
    5057  141.15    5057  142.95    5079  145.25    5114  153.15    5207  152.28
    5491  153.26    5624  152.89
#Mann= 3 ,-1 , 0
    1260     .99       0    4926     .03       0    5114     .99       0
#XS Ineff= 2 , 0
       0    4998   152.1    5002       0   152.1
Permanent Ineff=
       F       F
#Block Obstruct= 2 , 0
         1137.25  154.15
Bank Sta=4926,5114
XS Rating Curve= 0
Exp/Cntr=.8,.6

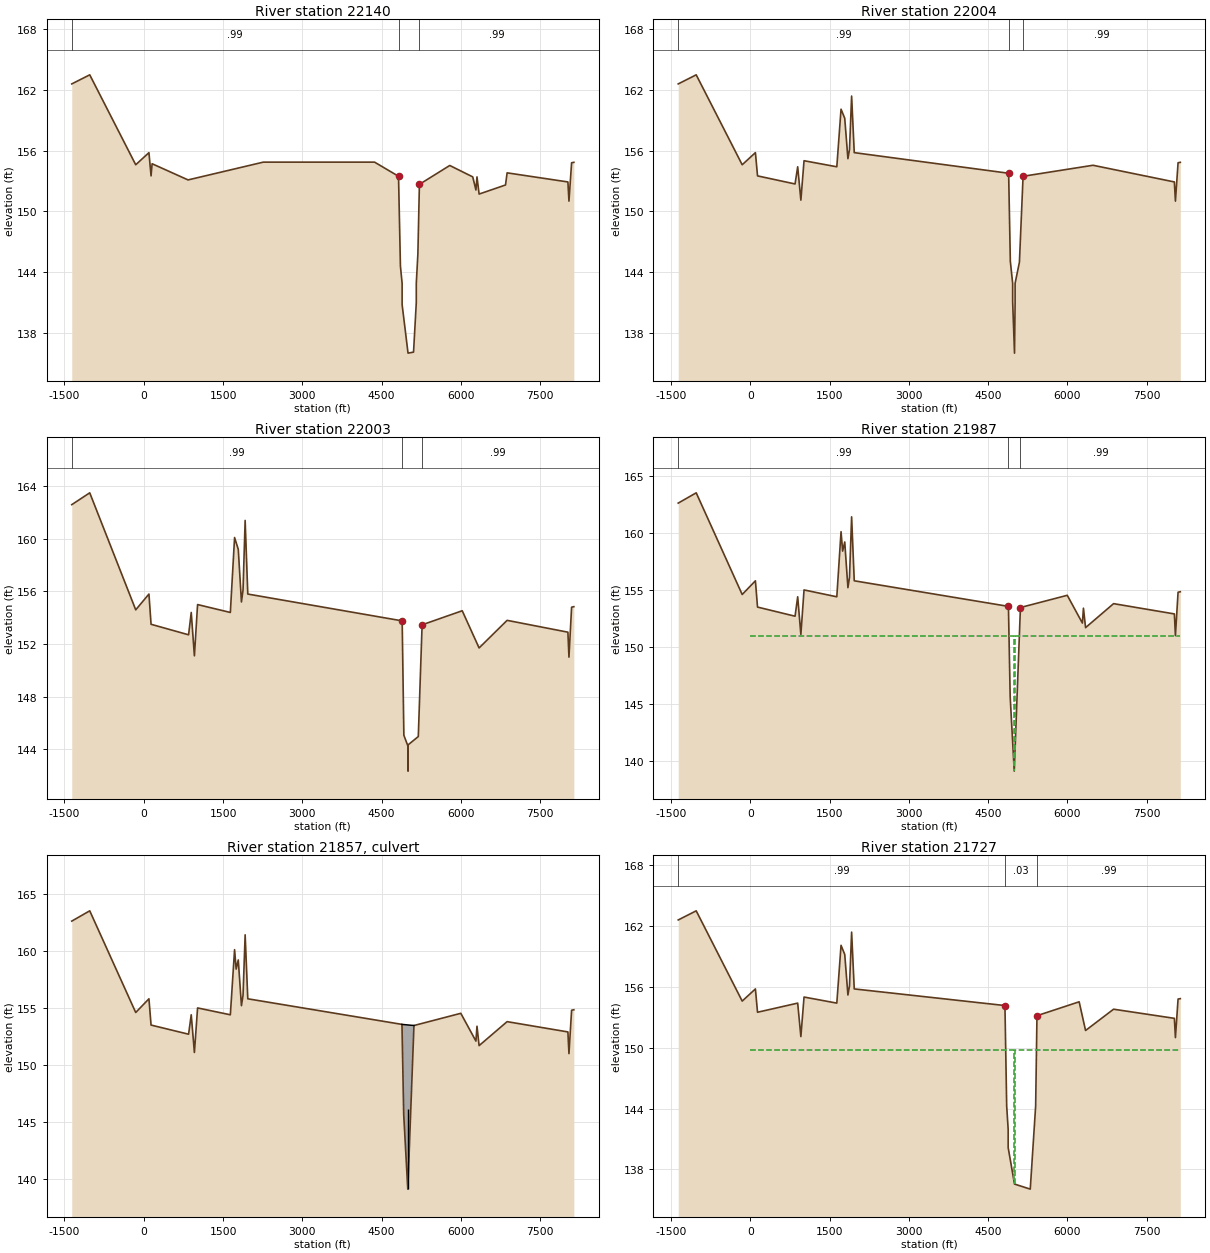
Type RM Length L Ch R = 1 ,22140   ,147,174,219
XS GIS Cut Line= 6
      3011322.56     13926499.25       3009933.9     13925012.98
      3007324.59     13922207.94      3007143.88     13922023.71
      3007134.85     13921955.07      3005872.16     13918917.76
#Sta/Elev= 30
 -1361.7   162.6 -1021.7   163.5  -151.7   154.6    98.3   155.8   138.3   153.5
   158.3   154.7   838.3   153.1    2262  154.86    4367  154.86    4820  153.46
    4856  144.56    4888  142.86    4888  140.76    5000  135.96    5104  136.06
    5156  140.96    5156  142.86    5186  145.76    5215  152.66    5789  154.53
  6224.2   153.4  6284.2   152.1  6304.2   153.4  6344.2   151.7  6844.2   152.6
  6874.2   153.8  8024.2   152.9  8044.2     151  8094.2   154.8 8136.66  154.84
#Mann= 3 ,-1 , 0
 -1361.7     .99       0    4820     .03       0    5215     .99       0
#Block Obstruct= 2 , 0
         1137.25  154.15
Bank Sta=4820,5215
XS Rating Curve= 0
Exp/Cntr=.3,.1

Type RM Length L Ch R = 1 ,22004   ,1,1,1
XS GIS Cut Line= 4
      3011496.54   13926502.5288    3007248.8819   13921953.1695
    3007239.8204   13921884.3329    3006007.0701   13918919.5419
#Sta/Elev= 30
 -1361.7   162.6 -1021.7   163.5  -151.7   154.6    98.3   155.8   138.3   153.5
   848.3   152.7   898.3   154.4   958.3   151.1  1018.3     155  1638.3   154.4
  1718.3   160.1  1788.3   159.2  1848.3   155.2  1878.3   156.1  1918.3   161.4
  1968.3   155.8    4889  153.76    4921  145.06    4965  142.86    4965  141.06
    5000  135.96    5011  140.86    5011  142.86    5093  144.96    5162  153.46
    6485  154.55  8024.2   152.9  8044.2     151  8094.2   154.8 8136.66  154.84
#Mann= 3 ,-1 , 0
 -1361.7     .99       0    4889     .03       0    5162     .99       0
#Block Obstruct= 2 , 0
         1137.25  154.15
Bank Sta=4889,5162
XS Rating Curve= 0
Exp/Cntr=.3,.1

Type RM Length L Ch R = 1 ,22003   ,16,16,16
XS GIS Cut Line= 4
    3011497.2621   13926501.8369    3007249.8298   13921952.7078
    3007240.7945   13921884.0708    3006007.9976    13918919.168
#Sta/Elev= 30
 -1361.7   162.6 -1021.7   163.5  -151.7   154.6    98.3   155.8   138.3   153.5
   848.3   152.7   898.3   154.4   958.3   151.1  1018.3     155  1638.3   154.4
  1718.3   160.1  1788.3   159.2  1848.3   155.2  1878.3   156.1  1918.3   161.4
  1968.3   155.8    4889  153.76    4921  145.06  4998.5  144.23    5000  142.33
  5001.5  144.33    5194  144.96    5266  153.46    6025  154.53  6344.2   151.7
  6874.2   153.8  8024.2   152.9  8044.2     151  8094.2   154.8 8136.66  154.84
#Mann= 3 ,-1 , 0
 -1361.7     .99       0    4889     .03       0    5266     .99       0
#Block Obstruct= 2 , 0
         1137.25  154.15
Bank Sta=4889,5266
XS Rating Curve= 0
Exp/Cntr=.3,.1

Type RM Length L Ch R = 1 ,21987   ,260,260,260
XS GIS Cut Line= 4
     3011510.888   13926489.7518      3007263.32   13921940.4775
    3007254.2847   13921871.8405    3006024.5044   13918914.2449
#Sta/Elev= 30
 -1361.7   162.6 -1021.7   163.5  -151.7   154.6    98.3   155.8   138.3   153.5
   848.3   152.7   898.3   154.4   958.3   151.1  1018.3     155  1638.3   154.4
  1718.3   160.1  1748.3   158.4  1788.3   159.2  1848.3   155.2  1878.3   156.1
  1918.3   161.4  1968.3   155.8    4885  153.56    4918  145.66    4995  139.14
    5112  153.46    5998  154.53  6284.2   152.1  6304.2   153.4  6344.2   151.7
  6874.2   153.8  8024.2   152.9  8044.2     151  8094.2   154.8 8136.66  154.84
#Mann= 3 ,-1 , 0
 -1361.7     .99       0    4885     .03       0    5112     .99       0
#XS Ineff= 2 , 0
       0  4994.5     151  5004.5       0     151
Permanent Ineff=
       F       F
#Block Obstruct= 2 , 0
         1137.25  154.15
Bank Sta=4885,5112
XS Rating Curve= 0
Exp/Cntr=.3,.1

Type RM Length L Ch R = 2 ,21857   ,,,
Bridge Culvert--1,0,-1,-1, 0
Deck Dist Width WeirC Skew NumUp NumDn MinLoCord MaxHiCord MaxSubmerge Is_Ogee
41,80,2.6,0, 2, 2, , , .95, 0, 0,0,,
    4885    5112
  153.56  153.46
  134.25  134.25
    4819    5504
  154.16  154.43
  134.25  134.25
BR Coef=-1 , 0 , 0 ,, 0 ,,,.8,-1,,0,
WSPro=,,,, 1 ,,,, 0 ,,,, 0 ,,,,-1 ,-1 ,-1 , 0 , 0 , 0 , 0 , 0
Culvert=2,7,9,249,.013,.4,1,8,1,139.14,5000,137.35,5000,Culvert #1  , 0 ,4
Culvert Bottom n=.013
BC Design=,, 0 ,, 0 ,,,,,,
BC HTab HWMax=163.5

Type RM Length L Ch R = 1 ,21727   ,764,764,764
BEGIN DESCRIPTION:
Cross Section K145-00-00-X08A   Note:
The  .2% flood appears to spill towards the south on the right overbank at this location.  Flows on the  right overbank are modeled as ineffective in the RAS model.  The mapping has been truncated to a low road ditch.
END DESCRIPTION:
XS GIS Cut Line= 5
      3011725.01     13926396.43       3008661.5     13923111.99
      3007403.37     13921763.74      3007400.97     13921713.38
    3006204.2013   13918839.1272
#Sta/Elev= 30
 -1361.7   162.6 -1021.7   163.5  -151.7   154.6    98.3   155.8   138.3   153.5
   898.3   154.4   958.3   151.1  1018.3     155  1638.3   154.4  1718.3   160.1
  1788.3   159.2  1848.3   155.2  1878.3   156.1  1918.3   161.4  1968.3   155.8
    4819  154.16    4852  144.26    4880  141.96    4880  140.16    5000  136.56
    5298  136.06    5400  144.26    5425  153.16    6223  154.53  6344.2   151.7
  6874.2   153.8  8024.2   152.9  8044.2     151  8094.2   154.8 8136.66  154.84
#Mann= 3 ,-1 , 0
 -1361.7     .99       0    4819     .03       0    5425     .99       0
#XS Ineff= 2 , 0
       0  4994.5  149.77  5004.5       0  149.77
Permanent Ineff=
       F       F
#Block Obstruct= 2 , 0
         1137.25  154.15
Bank Sta=4819,5425
XS Rating Curve= 0
Exp/Cntr=.3,.1

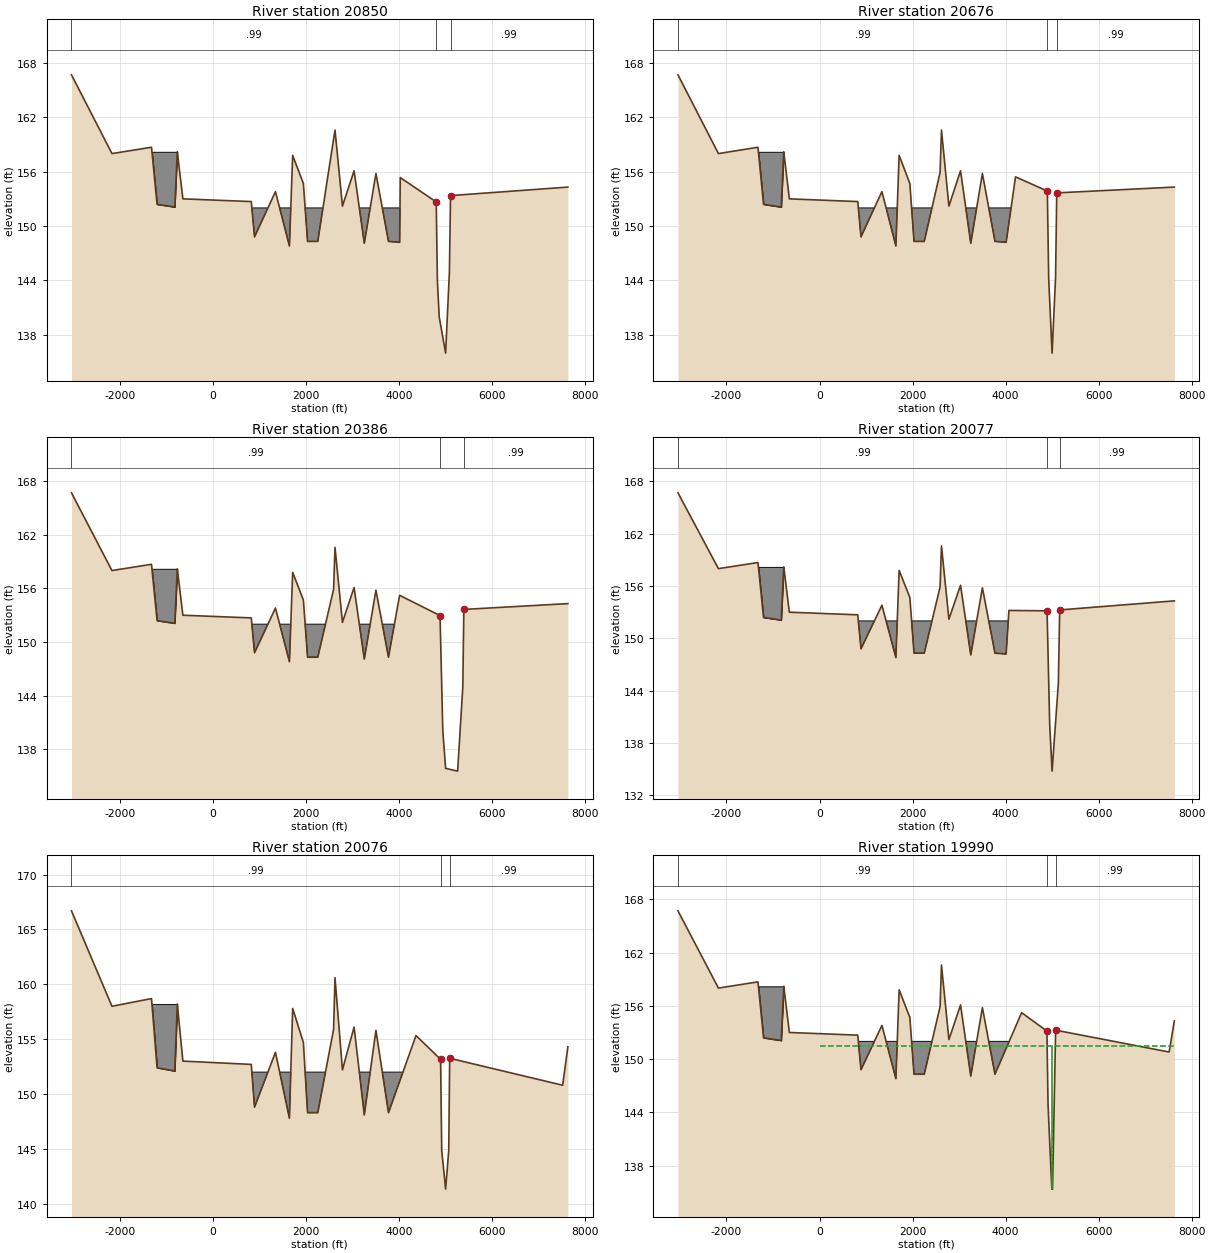
Type RM Length L Ch R = 1 ,20850   ,174,174,174
BEGIN DESCRIPTION:
The  .2% flood appears to spill towards the south on the right overbank at this location.  Flows on the  right overbank are modeled as ineffective in the RAS model.  The mapping has been truncated to a low road ditch.
END DESCRIPTION:
XS GIS Cut Line= 4
    3012378.4329    13927476.438    3011835.4932   13925293.9975
    3007032.3148   13920121.0542    3006405.2431   13918920.1846
#Sta/Elev= 30
 -3043.2   166.7 -2173.2     158 -1323.2   158.7 -1203.2   152.4  -823.2   152.1
  -768.1   158.2  -648.1     153   821.9   152.7   891.9   148.8  1341.9   153.8
  1641.9   147.8  1711.9   157.8  1941.9   154.7  2031.9   148.3  2251.9   148.3
  2621.9   160.6  2781.9   152.2  3031.9   156.1  3251.9   148.1  3501.9   155.8
  3771.9   148.3  4011.9   148.2    4025  155.35    4798  152.66    4823  143.96
    4862  139.96    5000  135.96    5081  144.86    5106  153.36 7627.84   154.3
#Mann= 3 ,-1 , 0
 -3043.2     .99       0    4798     .03       0    5106     .99       0
#Block Obstruct= 2 ,-1
   -1326  -768.1   158.2       0    4207     152
Bank Sta=4798,5106
XS Rating Curve= 0
Exp/Cntr=.3,.1

Type RM Length L Ch R = 1 ,20676   ,290,290,290
BEGIN DESCRIPTION:
The  .2% flood appears to spill towards the south on the right overbank at this location.  Flows on the  right overbank are modeled as ineffective in the RAS model.  The mapping has been truncated to a low road ditch.
END DESCRIPTION:
XS GIS Cut Line= 4
    3012496.1638   13927350.4434    3011953.2241    13925168.003
    3007150.0458   13919995.0596    3006413.2989   13918858.1732
#Sta/Elev= 30
 -3043.2   166.7 -2173.2     158 -1323.2   158.7 -1203.2   152.4  -823.2   152.1
  -768.1   158.2  -648.1     153   821.9   152.7   891.9   148.8  1341.9   153.8
  1641.9   147.8  1711.9   157.8  1941.9   154.7  2031.9   148.3  2251.9   148.3
  2591.9   155.9  2621.9   160.6  2781.9   152.2  3031.9   156.1  3251.9   148.1
  3501.9   155.8  3771.9   148.3  4011.9   148.2    4214  155.43    4898  153.86
    4927  144.16    5000  135.96    5075  144.36    5100  153.66 7627.84   154.3
#Mann= 3 ,-1 , 0
 -3043.2     .99       0    4898     .03       0    5100     .99       0
#Block Obstruct= 2 ,-1
   -1326  -768.1   158.2       0    4207     152
Bank Sta=4898,5100
XS Rating Curve= 0
Exp/Cntr=.3,.1

Type RM Length L Ch R = 1 ,20386   ,383,383,383
BEGIN DESCRIPTION:
Cross Section K145-00-00-X8   Note:
The  .2% flood appears to spill towards the south on the right overbank at this location.  Flows on the  right overbank are modeled as ineffective in the RAS model.  The mapping has been truncated to a low road ditch.
END DESCRIPTION:
XS GIS Cut Line= 3
    3012669.0793   13927115.9267    3012126.1396   13924933.4863
    3006420.9026   13918749.8022
#Sta/Elev= 30
 -3043.2   166.7 -2173.2     158 -1323.2   158.7 -1203.2   152.4  -823.2   152.1
  -768.1   158.2  -648.1     153   821.9   152.7   891.9   148.8  1341.9   153.8
  1641.9   147.8  1711.9   157.8  1941.9   154.7  2031.9   148.3  2251.9   148.3
  2591.9   155.9  2621.9   160.6  2781.9   152.2  3031.9   156.1  3251.9   148.1
  3501.9   155.8  3771.9   148.3    4011  155.23    4880  152.96    4939  140.06
    5000  135.86    5258  135.55    5369  144.95    5392  153.65 7627.84   154.3
#Mann= 3 ,-1 , 0
 -3043.2     .99       0    4880     .03       0    5392     .99       0
#Block Obstruct= 2 ,-1
   -1326  -768.1   158.2       0    4207     152
Bank Sta=4880,5392
XS Rating Curve= 0
Exp/Cntr=.3,.1

Type RM Length L Ch R = 1 ,20077   ,1,1,1
BEGIN DESCRIPTION:
The  .2% flood appears to spill towards the south on the right overbank at this location.  Flows on the  right overbank are modeled as ineffective in the RAS model.  The mapping has been truncated to a low road ditch.
END DESCRIPTION:
XS GIS Cut Line= 3
    3012773.1304   13926825.7962    3012435.1476   13924700.2141
    3006667.8598   13918461.9036
#Sta/Elev= 30
 -3043.2   166.7 -2173.2     158 -1323.2   158.7 -1203.2   152.4  -823.2   152.1
  -768.1   158.2  -648.1     153   821.9   152.7   891.9   148.8  1341.9   153.8
  1641.9   147.8  1711.9   157.8  1941.9   154.7  2031.9   148.3  2251.9   148.3
  2591.9   155.9  2621.9   160.6  2781.9   152.2  3031.9   156.1  3251.9   148.1
  3501.9   155.8  3771.9   148.3  4011.9   148.2  4071.9   153.2    4892  153.16
    4948  140.16    5000  134.76    5135  144.86    5163  153.26 7627.84   154.3
#Mann= 3 ,-1 , 0
 -3043.2     .99       0    4892     .03       0    5163     .99       0
#Block Obstruct= 2 ,-1
   -1326  -768.1   158.2       0    4207     152
Bank Sta=4892,5163
XS Rating Curve= 0
Exp/Cntr=.3,.1

Type RM Length L Ch R = 1 ,20076   ,12,12,12
BEGIN DESCRIPTION:
The  .2% flood appears to spill towards the south on the right overbank at this location.  Flows on the  right overbank are modeled as ineffective in the RAS model.  The mapping has been truncated to a low road ditch.
END DESCRIPTION:
XS GIS Cut Line= 3
     3012774.105   13926825.5561    3012436.0876   13924699.7578
    3006668.5621   13918461.1901
#Sta/Elev= 30
 -3043.2   166.7 -2173.2     158 -1323.2   158.7 -1203.2   152.4  -823.2   152.1
  -768.1   158.2  -648.1     153   821.9   152.7   891.9   148.8  1341.9   153.8
  1641.9   147.8  1711.9   157.8  1941.9   154.7  2031.9   148.3  2251.9   148.3
  2591.9   155.9  2621.9   160.6  2781.9   152.2  3031.9   156.1  3251.9   148.1
  3501.9   155.8  3771.9   148.3    4363  155.33    4892  153.16    4916  144.86
    5000  141.33    5067  144.86    5087  153.26    7516   150.8 7627.84   154.3
#Mann= 3 ,-1 , 0
 -3043.2     .99       0    4892     .03       0    5087     .99       0
#Block Obstruct= 2 ,-1
   -1326  -768.1   158.2       0    4207     152
Bank Sta=4892,5087
XS Rating Curve= 0
Exp/Cntr=.3,.1

Type RM Length L Ch R = 1 ,19990   ,340,340,340
BEGIN DESCRIPTION:
The  .2% flood appears to spill towards the south on the right overbank at this location.  Flows on the  right overbank are modeled as ineffective in the RAS model.  The mapping has been truncated to a low road ditch.
END DESCRIPTION:
XS GIS Cut Line= 3
    3012785.9562   13926823.6717    3012447.3677   13924694.2819
    3006670.3559   13918445.4532
#Sta/Elev= 30
 -3043.2   166.7 -2173.2     158 -1323.2   158.7 -1203.2   152.4  -823.2   152.1
  -768.1   158.2  -648.1     153   821.9   152.7   891.9   148.8  1341.9   153.8
  1641.9   147.8  1711.9   157.8  1941.9   154.7  2031.9   148.3  2251.9   148.3
  2591.9   155.9  2621.9   160.6  2781.9   152.2  3031.9   156.1  3251.9   148.1
  3501.9   155.8  3771.9   148.3    4345  155.23    4889  153.16    4913  144.86
  4994.5  135.36  5009.5  135.36    5076  153.26    7516   150.8 7627.84   154.3
#Mann= 3 ,-1 , 0
 -3043.2     .99       0    4889     .03       0    5076     .99       0
#XS Ineff= 2 , 0
       0  4990.5   151.5  5008.5       0   151.5
Permanent Ineff=
       F       F
#Block Obstruct= 2 ,-1
   -1326  -768.1   158.2       0    4207     152
Bank Sta=4889,5076
XS Rating Curve= 0
Exp/Cntr=.3,.1

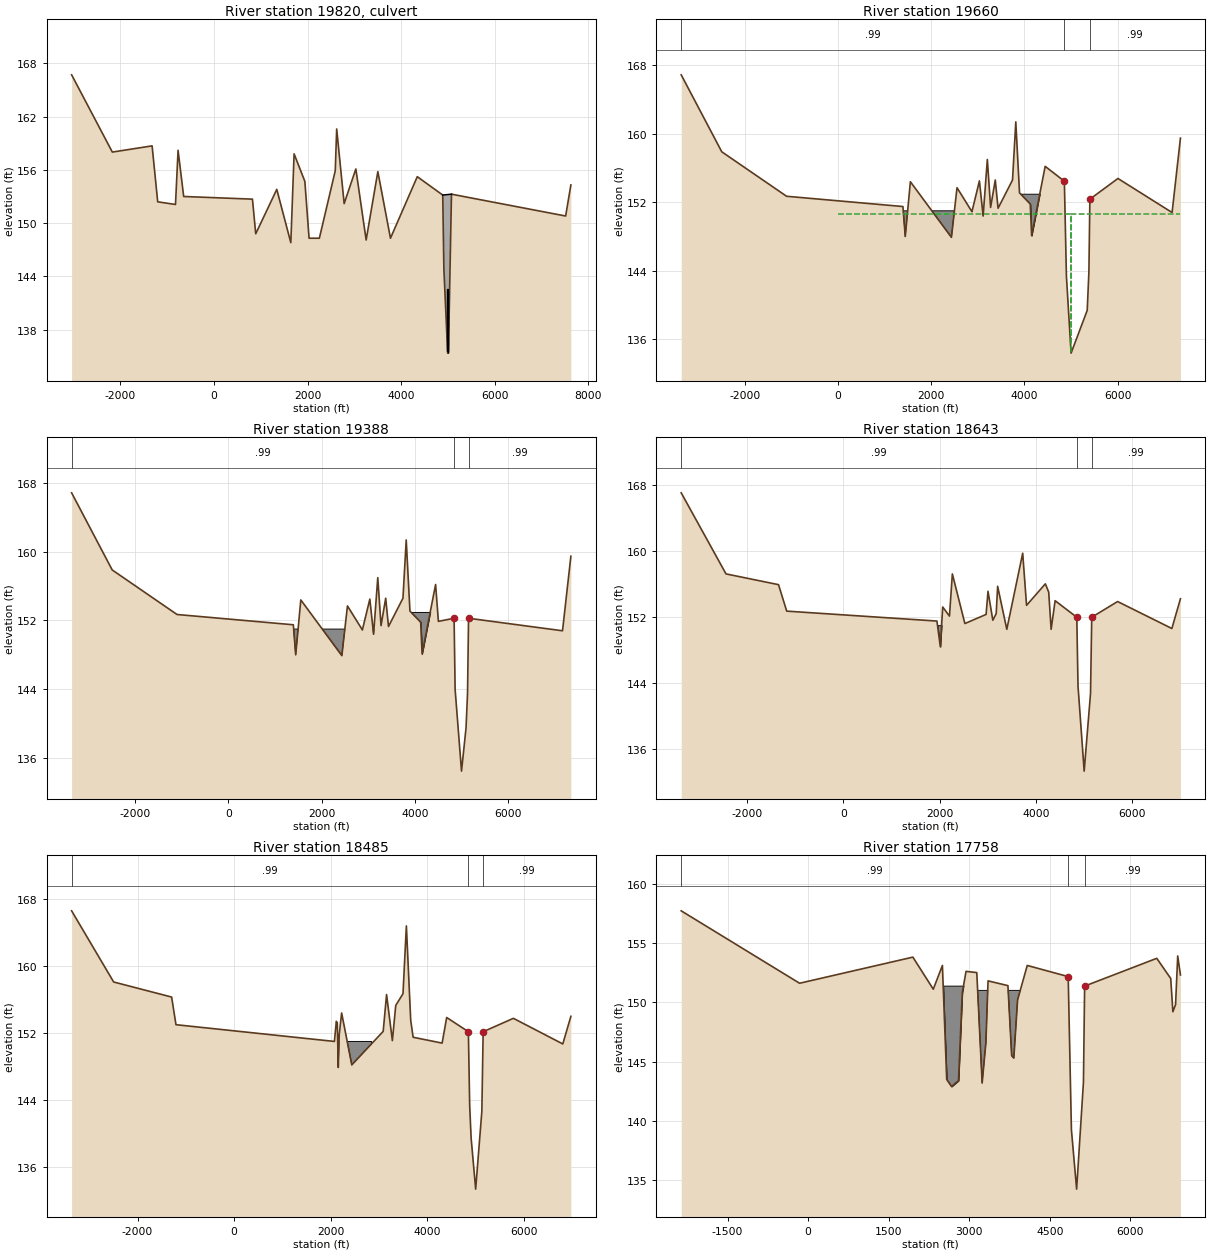
Type RM Length L Ch R = 2 ,19820   ,,,
Bridge Culvert--1,0,-1,-1, 0
Deck Dist Width WeirC Skew NumUp NumDn MinLoCord MaxHiCord MaxSubmerge Is_Ogee
83,100,2.6,0, 2, 2, , , .95, 0, 0,0,,
    4889    5076
  153.16  153.26
  134.25  134.25
    4856    5482
  154.46  154.66
  134.25  134.25
BR Coef=-1 , 0 , 0 ,, 0 ,,,.8,-1,,0,
WSPro=,,,, 1 ,,,, 0 ,,,, 0 ,,,,-1 ,-1 ,-1 , 0 , 0 , 0 , 0 , 0
Culvert=2,7,9,307,.013,.4,1,8,1,135.57,4995,136.03,4995,Culvert #1  , 0 ,9
Culvert Bottom n=.013
Culvert=2,7,9,307,.011,.5,1,8,1,135.38,5005,135.77,5005,Culvert #2  , 0 ,9
Culvert Bottom n=.011
BC Design=,, 0 ,, 0 ,,,,,,
BC HTab HWMax=166.7

Type RM Length L Ch R = 1 ,19660   ,273,273,273
BEGIN DESCRIPTION:
Cross Section K145-00-00-X7   Note:
The  .2% flood appears to spill towards the south on the right overbank at this location.  Flows on the  right overbank are modeled as ineffective in the RAS model.  The mapping has been truncated to a low road ditch.
END DESCRIPTION:
XS GIS Cut Line= 5
      3012839.59     13927058.27      3012457.54     13924381.36
      3008729.94     13920192.01      3008669.71     13920134.24
      3007175.52     13918373.37
#Sta/Elev= 30
 -3359.5   166.9 -2489.5   157.9 -1099.5   152.7  1394.5   151.5  1444.5     148
  1554.5   154.4  2434.5   147.9  2554.5   153.7  2874.5   150.9  3034.5   154.5
  3114.5   150.4  3204.5     157  3274.5   151.4  3374.5   154.6  3434.5   151.3
  3744.5   154.6  3814.5   161.4  3894.5   153.1  4124.5   151.8  4154.5   148.1
  4444.5   156.2    4856  154.46    4900  143.36    5000  134.36    5346  139.36
    5382  143.86    5403  152.36    6005  154.78  7165.6   150.8    7345   159.5
#Mann= 3 ,-1 , 0
 -3359.5     .99       0    4856     .03       0    5403     .99       0
#XS Ineff= 2 , 0
       0  4990.5  150.67  5008.5       0  150.67
Permanent Ineff=
       F       F
#Block Obstruct= 2 ,-1
    3800    4444     153    1210    3350     151
Bank Sta=4856,5403
XS Rating Curve= 0
Exp/Cntr=.3,.1

Type RM Length L Ch R = 1 ,19388   ,701,720,697
BEGIN DESCRIPTION:
Cross Section K145-00-00-X7   Note:
The  .2% flood appears to spill towards the south on the right overbank at this location.  Flows on the  right overbank are modeled as ineffective in the RAS model.  The mapping has been truncated to a low road ditch.
END DESCRIPTION:
XS GIS Cut Line= 5
      3012877.45     13926980.02      3012489.82     13924359.46
      3010877.77      13922275.5      3009392.05     13920529.84
      3007344.63     13918153.49
#Sta/Elev= 30
 -3359.5   166.9 -2489.5   157.9 -1099.5   152.7  1394.5   151.5  1444.5     148
  1554.5   154.4  2434.5   147.9  2554.5   153.7  2874.5   150.9  3034.5   154.5
  3114.5   150.4  3204.5     157  3274.5   151.4  3374.5   154.6  3434.5   151.3
  3744.5   154.6  3814.5   161.4  3894.5   153.1  4124.5   151.8  4154.5   148.1
  4444.5   156.2  4504.5   151.9    4841  152.26    4863  143.96    5000  134.42
    5097  139.46    5129  143.46    5151  152.26  7165.6   150.8    7345   159.5
#Mann= 3 ,-1 , 0
 -3359.5     .99       0    4841     .03       0    5151     .99       0
#Block Obstruct= 2 ,-1
    3800    4444     153    1210    3350     151
Bank Sta=4841,5151
XS Rating Curve= 0
Exp/Cntr=.3,.1

Type RM Length L Ch R = 1 ,18643   ,159,159,159
BEGIN DESCRIPTION:
Cross Section K145-Interpolated-5
END DESCRIPTION:
XS GIS Cut Line= 5
      3012955.05      13926991.7      3012533.22     13924326.92
      3009510.55     13919603.31      3009450.13      13919479.2
      3008366.28     13917896.46
#Sta/Elev= 30
 -3363.9     167 -2433.9   157.2 -1343.9   155.9 -1173.9   152.7  1944.1   151.5
  2014.1   148.4  2064.1   153.2  2204.1   152.1  2264.1   157.2  2524.1   151.2
  2964.1   152.3  3004.1   155.1  3104.1   151.6  3174.1   152.4  3204.1   155.7
  3394.1   150.5  3724.1   159.7  3804.1   153.4  4194.1     156  4264.1     155
  4314.1   150.5    4397  153.96    4847  151.96    4872  143.66    5000  133.36
    5132  142.76    5157  151.96    5694  153.86    6820   150.6  6998.3   154.2
#Mann= 3 ,-1 , 0
 -3363.9     .99       0    4847     .03       0    5157     .99       0
#Block Obstruct= 1 ,-1
    1760    2120     151
Bank Sta=4847,5157
XS Rating Curve= 0
Exp/Cntr=.3,.1

Type RM Length L Ch R = 1 ,18485   ,729,729,729
BEGIN DESCRIPTION:
Cross Section K145-Interpolated-4
END DESCRIPTION:
XS GIS Cut Line= 5
      3013027.08     13926971.13      3012612.81     13924283.59
      3009663.21     13919552.66      3009597.32       13919426.
      3008613.21     13917803.86
#Sta/Elev= 30
 -3363.6   166.6 -2493.6   158.1 -1293.6   156.3 -1203.6     153  2075.7     151
  2115.7   153.4  2135.7   153.2  2155.7   147.9  2175.7   151.8  2225.7   154.4
  2435.7   148.2  3085.7   152.2  3155.7   156.6  3275.7   151.1  3345.7   155.3
  3495.7   156.7  3565.7   164.8  3655.7   153.5  3705.7   151.5  4305.7   150.8
    4400  153.86    4849  152.16    4876  143.36    4906  139.46    5000  133.36
    5128  142.66    5155  152.16    5781  153.76  6803.6   150.7  6970.9     154
#Mann= 3 ,-1 , 0
 -3363.6     .99       0    4849     .03       0    5155     .99       0
#Block Obstruct= 1 ,-1
    2000    2843     151
Bank Sta=4849,5155
XS Rating Curve= 0
Exp/Cntr=.3,.1

Type RM Length L Ch R = 1 ,17758   ,62,62,62
BEGIN DESCRIPTION:
Cross Section K145-Interpolated-3
END DESCRIPTION:
XS GIS Cut Line= 5
      3013623.82     13925787.92      3013048.44     13924810.11
      3010351.89     13919312.96      3010251.87     13919106.94
      3009426.02      13917495.2
#Sta/Elev= 30
   -2364   157.7  -159.5   151.6  1950.5   153.8  2330.5   151.1  2500.5   153.1
  2580.5   143.5  2670.5   142.9  2800.5   143.4  2870.5   150.8  2940.5   152.6
  3140.5   152.5  3240.5   143.2  3310.5   146.6  3350.5   151.8  3720.5   151.4
  3790.5   145.5  3830.5   145.3  3900.5   150.2  4080.5   153.1    4843  152.16
    4903  139.26    5000  134.26    5127  143.26    5149  151.36  6492.5   153.7
  6752.5     152  6792.5   149.2  6842.5   149.8  6882.5   153.9  6933.5   152.3
#Mann= 3 ,-1 , 0
   -2364     .99       0    4843     .03       0    5149     .99       0
#Block Obstruct= 2 ,-1
    2445    3058   151.4    3060    4090     151
Bank Sta=4843,5149
XS Rating Curve= 0
Exp/Cntr=.3,.1