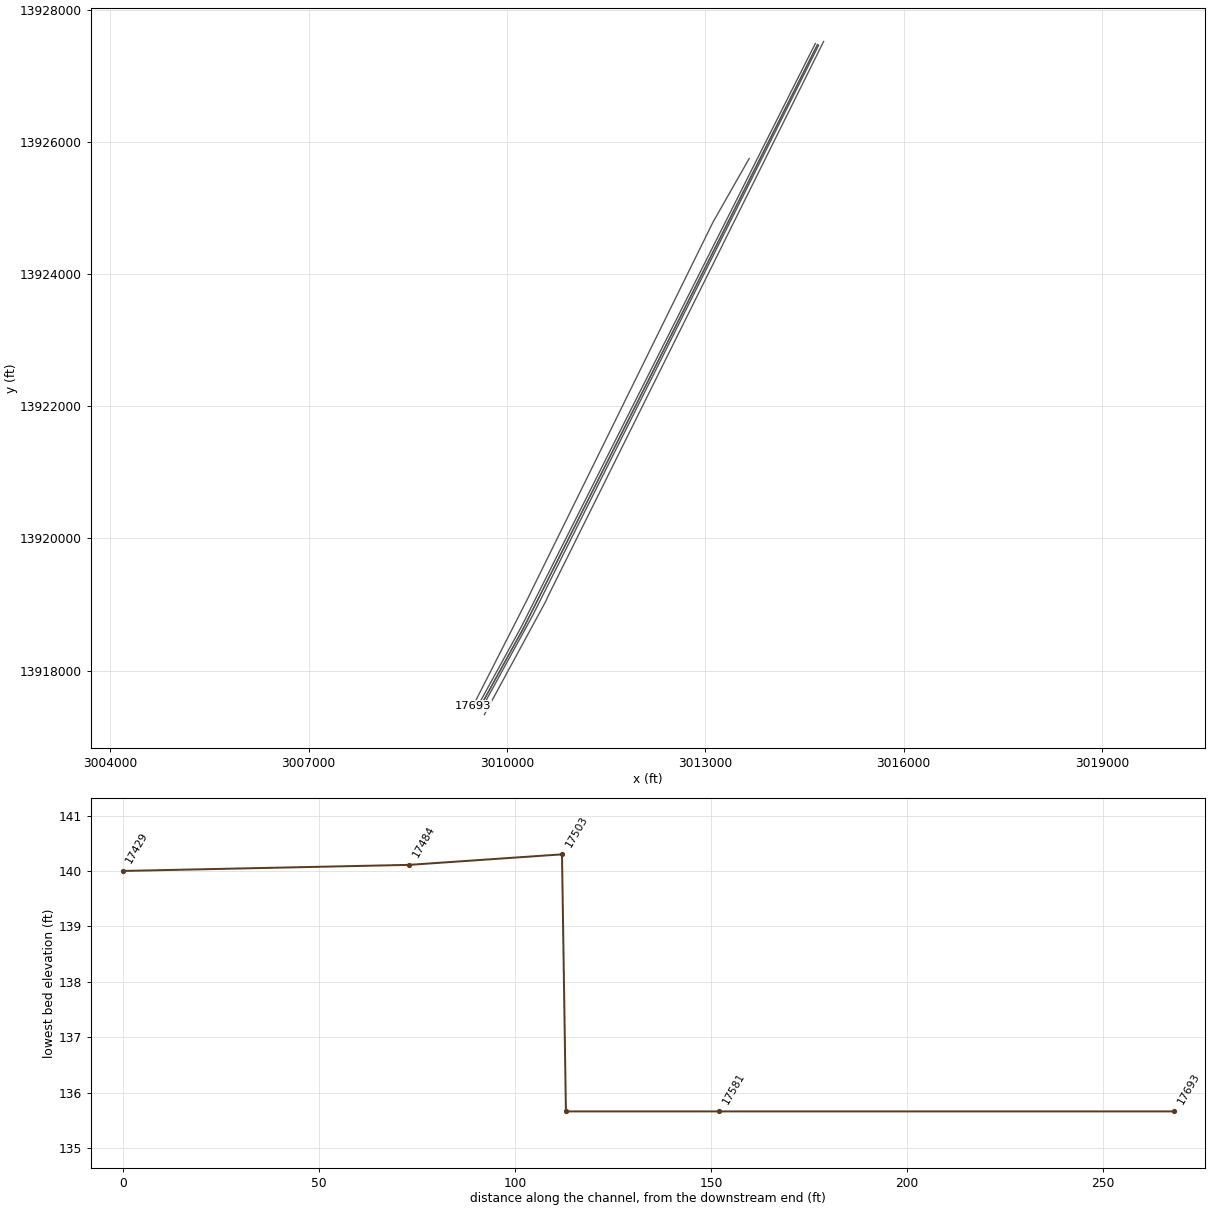
HEC-RAS study k145-00-00.prj: K145-00-00

--- k145-00-00.g01 (geometry) --- (continued)

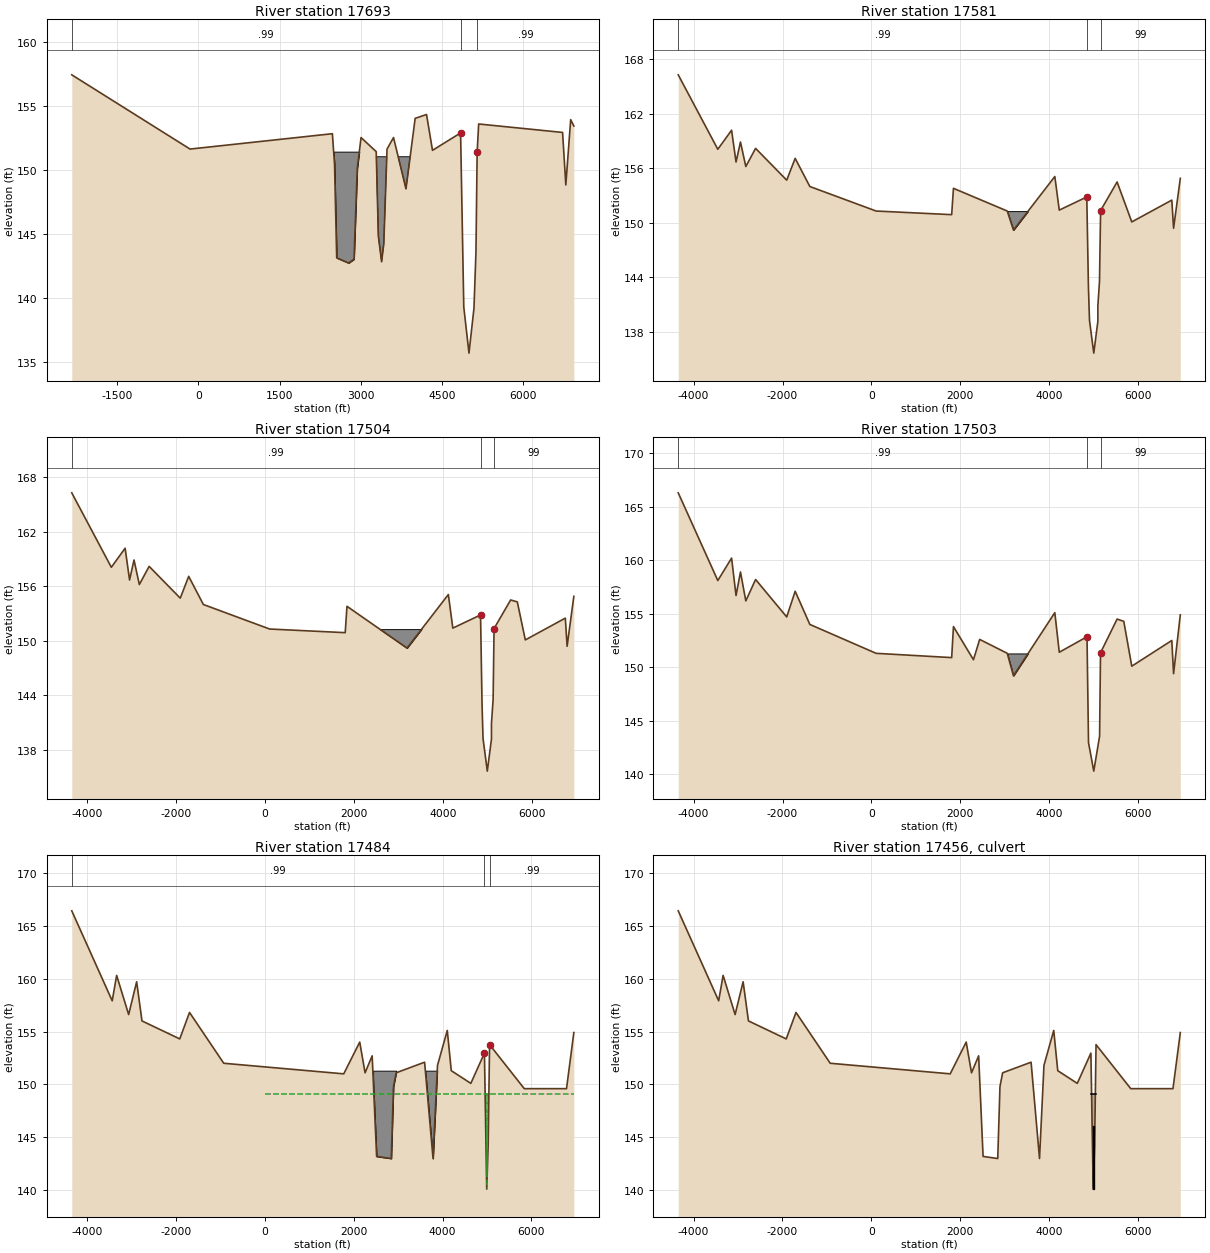
Type RM Length L Ch R = 1 ,17693   ,116,116,116
BEGIN DESCRIPTION:
Cross Section K145-Interpolated-2
END DESCRIPTION:
XS GIS Cut Line= 5
      3013664.98     13925746.77      3013118.18     13924785.58
      3010396.64     13919256.79      3010326.25     13919111.52
      3009487.75     13917464.33
#Sta/Elev= 30
 -2340.1   157.4  -154.3   151.6  2475.7   152.8  2515.7   150.4  2555.7   143.1
  2775.7   142.7  2875.7     143  2935.7   150.1  3005.7   152.5  3285.7   151.4
  3325.7   144.8  3385.7   142.8  3425.7   144.2  3485.7   151.6  3605.7   152.5
  3835.7   148.5  4005.7     154  4215.7   154.3  4325.7   151.5    4845  152.86
    4904  139.26    5000  135.66    5092  139.16    5129  143.56    5151  151.36
    5179  153.56  6729.5   152.9  6789.5   148.8  6879.5   153.9  6937.8   153.4
#Mann= 3 ,-1 , 0
 -2340.1     .99       0    4845     .03       0    5151     .99       0
#Block Obstruct= 2 ,-1
    2424    3070   151.4    3071    4143     151
Bank Sta=4845,5151
XS Rating Curve= 0
Exp/Cntr=.5,.3

Type RM Length L Ch R = 1 ,17581   ,39,39,39
XS GIS Cut Line= 4
      3014665.08     13927486.79      3012518.94     13923223.66
      3010220.34     13918664.31      3009544.51     13917436.29
#Sta/Elev= 30
 -4345.8  166.31 -3455.8  158.11 -3145.8  160.21 -3045.8  156.71 -2945.8  158.91
 -2825.8  156.21 -2605.8  158.21 -1905.8  154.71 -1715.8  157.11 -1385.8  154.01
   104.2  151.31  1804.2  150.91  1844.2  153.81  3054.2  151.31  3194.2  149.21
  4124.2  155.11  4224.2  151.41    4843  152.86    4880  142.96    4904  139.26
    5000  135.66    5092  139.16    5092  140.86    5129  143.56    5154  151.36
    5525  154.51    5855  150.11    6755  152.51    6795  149.41  6946.5  154.91
#Mann= 3 ,-1 , 0
 -4345.8     .99       0    4843     .03       0    5154      99       0
#Block Obstruct= 1 ,-1
    2585    3576   151.3
Bank Sta=4843,5154
XS Rating Curve= 0
Exp/Cntr=.5,.3

Type RM Length L Ch R = 1 ,17504   ,1,1,1
XS GIS Cut Line= 3
    3014698.1539   13927470.1974    3010253.0672   13918647.0417
    3009576.9234   13917418.4512
#Sta/Elev= 30
 -4345.8  166.31 -3455.8  158.11 -3145.8  160.21 -3045.8  156.71 -2945.8  158.91
 -2825.8  156.21 -2605.8  158.21 -1905.8  154.71 -1715.8  157.11 -1385.8  154.01
   104.2  151.31  1804.2  150.91  1844.2  153.81  3194.2  149.21  4124.2  155.11
  4224.2  151.41    4848  152.86    4882  142.96    4904  139.26    5000  135.66
    5093  139.16    5093  140.86    5131  143.56    5152  151.36    5525  154.51
    5675   154.3    5855  150.11    6755  152.51    6795  149.41  6946.5  154.91
#Mann= 3 ,-1 , 0
 -4345.8     .99       0    4848     .03       0    5152      99       0
#Block Obstruct= 1 ,-1
    2585    3576   151.3
Bank Sta=4848,5152
XS Rating Curve= 0
Exp/Cntr=.5,.3

Type RM Length L Ch R = 1 ,17503   ,39,39,39
XS GIS Cut Line= 3
    3014699.0478   13927469.7491    3010253.9518    13918646.575
    3009577.7994   13917417.9691
#Sta/Elev= 30
 -4345.8  166.31 -3455.8  158.11 -3145.8  160.21 -3045.8  156.71 -2945.8  158.91
 -2825.8  156.21 -2605.8  158.21 -1905.8  154.71 -1715.8  157.11 -1385.8  154.01
   104.2  151.31  1804.2  150.91  1844.2  153.81  2294.2  150.71  2434.2  152.61
  3054.2  151.31  3194.2  149.21  4124.2  155.11  4224.2  151.41    4848  152.86
    4882  142.96    5000   140.3    5131  143.56    5152  151.36    5525  154.51
    5675   154.3    5855  150.11    6755  152.51    6795  149.41  6946.5  154.91
#Mann= 3 ,-1 , 0
 -4345.8     .99       0    4848     .03       0    5152      99       0
#Block Obstruct= 1 ,-1
    2585    3576   151.3
Bank Sta=4848,5152
XS Rating Curve= 0
Exp/Cntr=.5,.3

Type RM Length L Ch R = 1 ,17484   ,73,73,73
BEGIN DESCRIPTION:
U/S SECTION FOR 6X6 AS-BUILT BOX CULVERTS
END DESCRIPTION:
XS GIS Cut Line= 3
    3014715.0744   13927460.2634    3010390.5064   13918834.5291
    3009611.4778   13917414.3494
#Sta/Elev= 30
 -4343.6   166.4 -3433.6   157.9 -3333.6   160.3 -3063.6   156.6 -2883.6   159.7
 -2763.6     156 -1913.6   154.3 -1693.6   156.8  -923.6     152  1776.4     151
  2136.4     154  2256.4   151.1  2416.4   152.7  2516.4   143.2  2846.4     143
  2896.4   149.8  2956.4   151.1  3596.4   152.1  3786.4     143  3886.4   151.8
  4106.4   155.1  4196.4   151.3  4636.4   150.1  4942.6  152.96    4994  140.11
  5026.5  144.23  5058.2  153.76  5839.6   149.6  6789.6   149.6  6954.6   154.9
#Mann= 3 ,-1 , 0
 -4343.6     .99       0  4942.6     .04       0  5058.2     .99       0
#XS Ineff= 2 , 0
       0    4994   149.1    5007       0   149.1
Permanent Ineff=
       F       F
#Block Obstruct= 2 ,-1
  2437.3  2959.3   151.3  3597.3  3934.9   151.3
Bank Sta=4942.6,5058.2
XS Rating Curve= 0
Exp/Cntr=.5,.3

Type RM Length L Ch R = 2 ,17456   ,,,
Bridge Culvert--1,0,-1,-1, 0
Deck Dist Width WeirC Skew NumUp NumDn MinLoCord MaxHiCord MaxSubmerge Is_Ogee
1,22,2.6,0, 2, 2, , , .95, 0, 0,0,,
  4942.6  5058.2
   149.1   149.1
     139     139
  4942.6  5058.2
   149.1   149.1
     139     139
BR Coef=-1 , 0 , 0 ,, 0 ,,,.8,-1,,0,
WSPro=,,,, 1 ,,,, 0 ,,,, 0 ,,,,-1 ,-1 ,-1 , 0 , 0 , 0 , 0 , 0
Culvert=2,6,6,50,.013,.4,1,8,1,140.11,4997,140,4997,Culvert #2  , 0 ,3
Culvert Bottom n=.013
Culvert=2,6,6,50,.011,.5,1,8,1,140.11,5004,140.13,5004,Culvert #1  , 0 ,3
Culvert Bottom n=.011
BC Design=,, 0 ,, 0 ,,,,,,
BC HTab HWMax=166.4

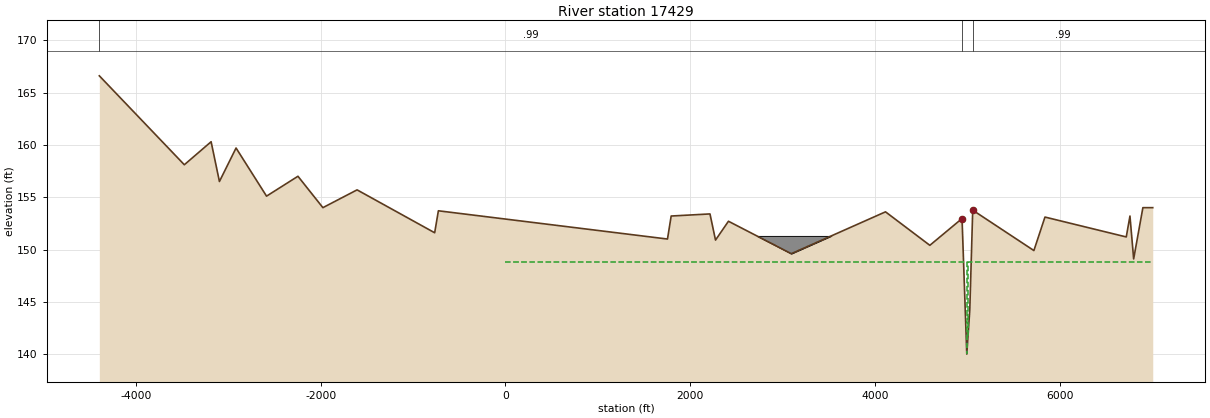
Type RM Length L Ch R = 1 ,17429   ,123,123,123
BEGIN DESCRIPTION:
BEGINNING OF IMPROVEMENTS D/S SECTION OF AS-BUILT 6X6 BOX CULVERTS
END DESCRIPTION:
XS GIS Cut Line= 4
       3014789.8     13927516.18      3010633.21     13919145.98
      3010586.96     13919045.31      3009659.59     13917333.89
#Sta/Elev= 30
 -4395.9   166.6 -3475.9   158.1 -3185.9   160.3 -3095.9   156.5 -2915.9   159.7
 -2585.9   155.1 -2245.9     157 -1975.9     154 -1605.9   155.7  -765.9   151.6
  -725.9   153.7  1754.1     151  1794.1   153.2  2214.1   153.4  2274.1   150.9
  2414.1   152.7  3094.1   149.6  4114.1   153.6  4594.1   150.4  4942.6  152.96
    4994     140  5026.5  144.23  5058.2  153.76  5720.3   149.9  5840.3   153.1
  6720.3   151.2  6760.3   153.2  6800.3   149.1  6900.3     154  7006.9     154
#Mann= 3 ,-1 , 0
 -4395.9     .99       0  4942.6     .04       0  5058.2     .99       0
#XS Ineff= 2 , 0
       0    4994  148.83    5007       0  148.83
Permanent Ineff=
       F       F
#Block Obstruct= 1 ,-1
 2424.71    3650   151.3
Bank Sta=4942.6,5058.2
XS Rating Curve= 0
Exp/Cntr=.5,.3