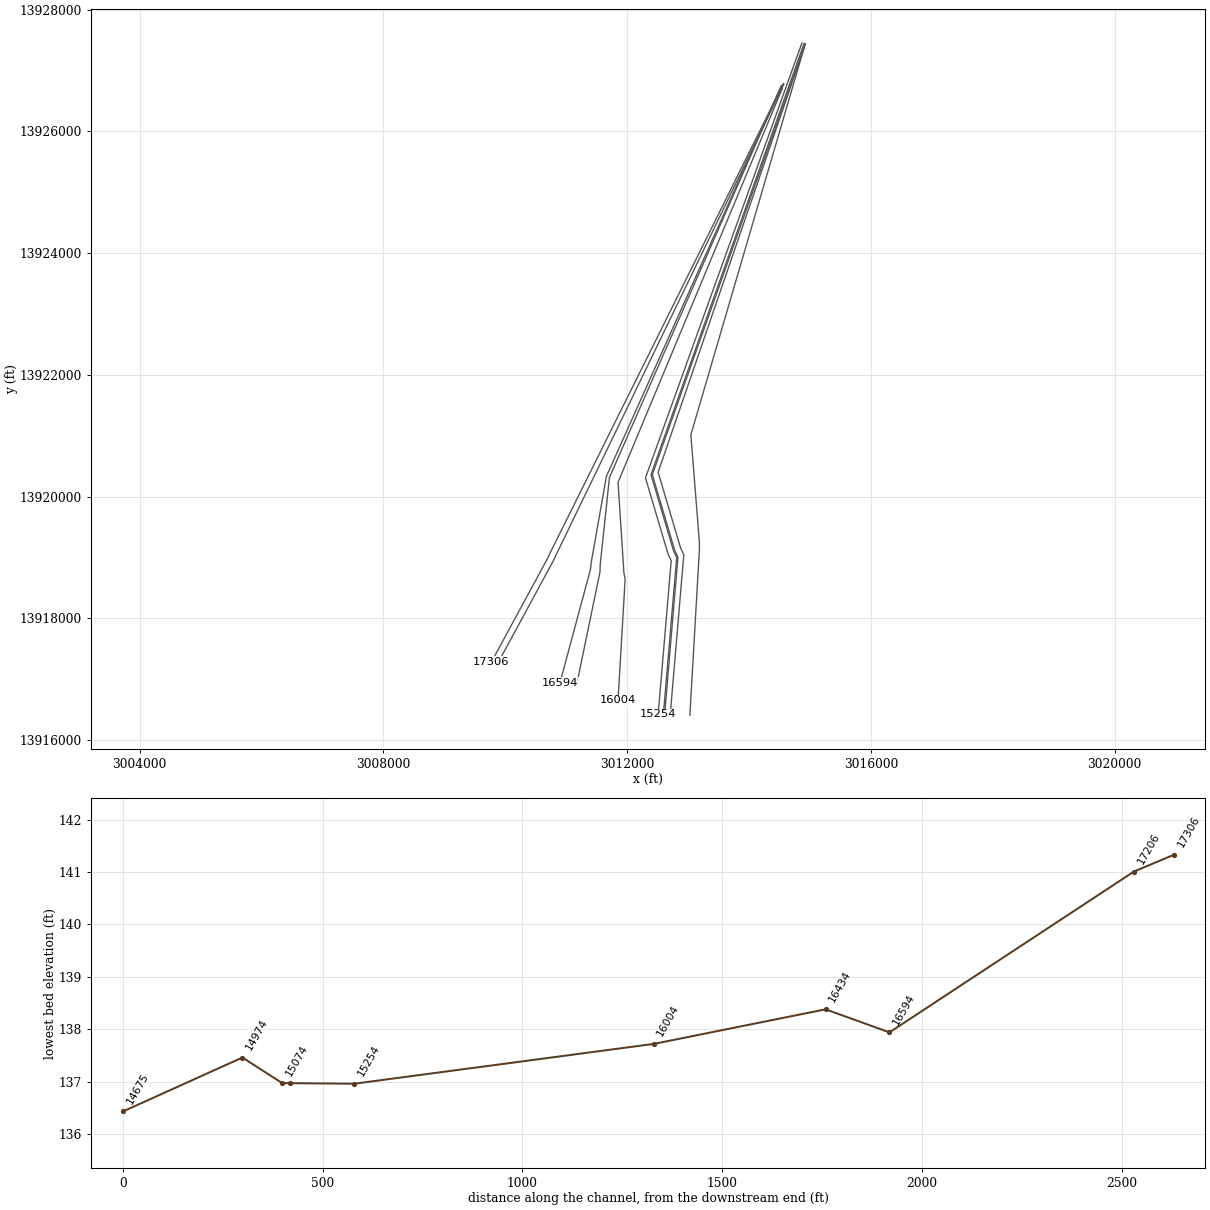
HEC-RAS study k145-00-00.prj: K145-00-00

--- k145-00-00.g01 (geometry) --- (continued)

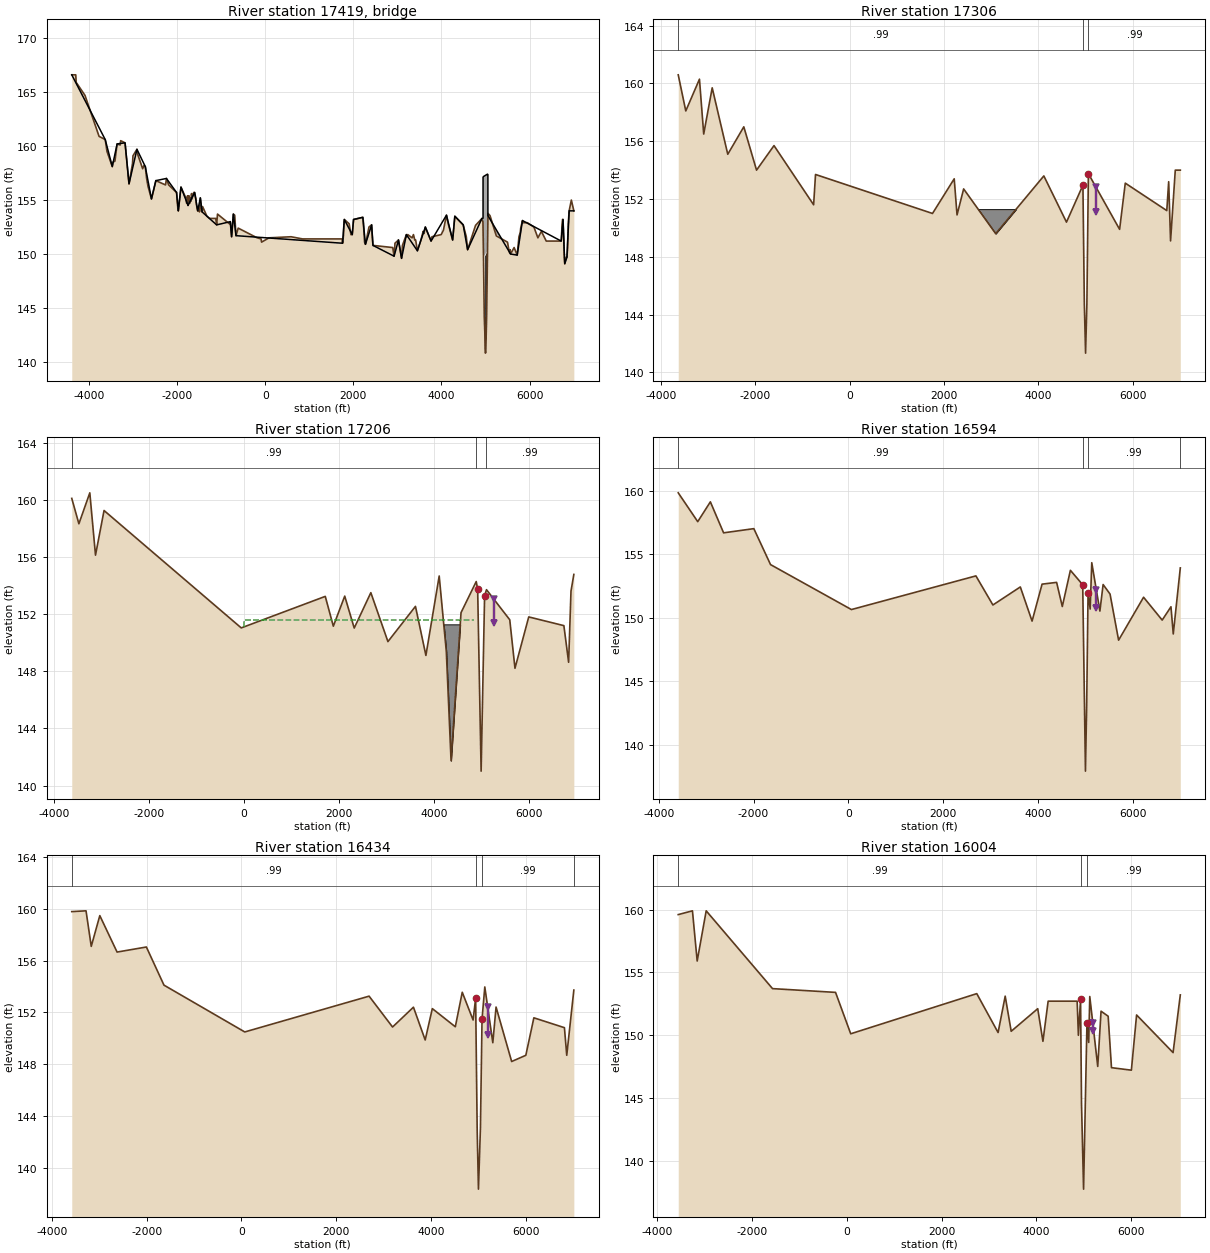
Type RM Length L Ch R = 3 ,17419   ,,,
BEGIN DESCRIPTION:
CYPRESS CHASE DRIVE
Structure ID: K145-00-00-S8
END DESCRIPTION:
Bridge Culvert--1,0,-1,-1, 0
Deck Dist Width WeirC Skew NumUp NumDn MinLoCord MaxHiCord MaxSubmerge Is_Ogee
10,95,2.6,0, 60, 60, , , .95, 0, ,,,
 -4395.9 -3635.9 -3475.9 -3365.9 -3185.9 -3095.9 -2915.9 -2725.9 -2585.9 -2485.9
 -2245.9 -2015.9 -1975.9 -1915.9 -1755.9 -1605.9 -1535.9 -1475.9 -1435.9 -1105.9
  -795.9  -765.9  -725.9  -665.9  1754.1  1794.1  1974.1  2004.1  2214.1  2274.1
  2414.1  2444.1  2924.1  3024.1  3094.1  3204.1  3454.1  3634.1  3764.1  4114.1
  4254.1  4304.1  4494.1  4594.1  4919.2 4944.79  4944.9 4954.81  5044.9  5054.9
 5055.01  5570.3  5720.3  5840.3  6720.3  6760.3  6800.3  6850.3  6900.3  7006.9
   166.6   160.6   158.1   160.2   160.3   156.5   159.7   158.1   155.1   156.8
     157   155.7     154   156.2   154.5   155.7     154   155.2   153.9   152.7
     153   151.6   153.7   151.7     151   153.2   151.8   153.2   153.4   150.9
   152.7   150.8   149.8   151.3   149.6   151.8   150.3   152.5   151.2   153.6
   151.3   153.5   152.7   150.4   153.3  153.32  157.12  157.18   157.4  157.36
  153.56     150   149.9   153.1   151.2   153.2   149.1   149.7     154     154
   166.6   160.6   158.1   160.2   160.3   156.5   159.7   158.1   155.1   156.8
     157   155.7     154   156.2   154.5   155.7     154   155.2   153.9   152.7
     153   151.6   153.7   151.7     151   153.2   151.8   153.2   153.4   150.9
   152.7   150.8   149.8   151.3   149.6   151.8   150.3   152.5   151.2   153.6
   151.3   153.5   152.7   150.4  153.29  152.39  152.36  149.76  150.26  152.89
  152.92     150   149.9   153.1   151.2   153.2   149.1   149.7     154     154
 -4395.9 -3635.9 -3475.9 -3365.9 -3185.9 -3095.9 -2915.9 -2725.9 -2585.9 -2485.9
 -2245.9 -2015.9 -1975.9 -1915.9 -1755.9 -1605.9 -1535.9 -1475.9 -1435.9 -1105.9
  -795.9  -765.9  -725.9  -665.9  1754.1  1794.1  1974.1  2004.1  2214.1  2274.1
  2414.1  2444.1  2924.1  3024.1  3094.1  3204.1  3454.1  3634.1  3764.1  4114.1
  4254.1  4304.1  4494.1  4594.1  4919.2 4944.79  4944.9 4954.81  5044.9  5054.9
 5055.01  5570.3  5720.3  5840.3  6720.3  6760.3  6800.3  6850.3  6900.3  7006.9
   166.6   160.6   158.1   160.2   160.3   156.5   159.7   158.1   155.1   156.8
     157   155.7     154   156.2   154.5   155.7     154   155.2   153.9   152.7
     153   151.6   153.7   151.7     151   153.2   151.8   153.2   153.4   150.9
   152.7   150.8   149.8   151.3   149.6   151.8   150.3   152.5   151.2   153.6
   151.3   153.5   152.7   150.4   153.3  153.32  157.12  157.18   157.4  157.36
  153.56     150   149.9   153.1   151.2   153.2   149.1   149.7     154     154
   166.6   160.6   158.1   160.2   160.3   156.5   159.7   158.1   155.1   156.8
     157   155.7     154   156.2   154.5   155.7     154   155.2   153.9   152.7
     153   151.6   153.7   151.7     151   153.2   151.8   153.2   153.4   150.9
   152.7   150.8   149.8   151.3   149.6   151.8   150.3   152.5   151.2   153.6
   151.3   153.5   152.7   150.4  153.29  152.39  152.36  149.76  150.26  152.89
  152.92     150   149.9   153.1   151.2   153.2   149.1   149.7     154     154
Pier Skew, UpSta & Num, DnSta & Num=  ,4984.4, 2 ,4984.4, 2 , 0 , 0 , 0 ,,
     1.3     1.3
  141.78  151.85
     1.3     1.3
  142.32  152.39
Pier Skew, UpSta & Num, DnSta & Num=  ,5014.5, 2 ,5014.5, 2 , 0 , 0 , 0 ,,
     1.3     1.3
  141.01  151.94
     1.3     1.3
  141.55  152.48
BR Coef= 1 , 1 , 1 ,1.25, 0 ,,,.8,0,2,0,
WSPro=,,,, 1 ,,,, 0 ,,,, 0 ,,,,-1 ,-1 ,-1 , 0 , 0 , 0 , 0 , 0
BR U #Sta/Elev= 194
 -4395.9   166.6 -4305.9   166.6 -4295.9   165.9 -4095.9   164.7 -3775.9   160.9
 -3635.9   160.6 -3595.9   159.5 -3475.9   158.1 -3465.9   158.5 -3415.9   158.6
 -3365.9   160.2 -3295.9   160.1 -3285.9   160.5 -3185.9   160.3 -3095.9   156.5
 -3015.9   158.4 -3005.9   159.1 -2915.9   159.7 -2895.9   159.2 -2785.9   157.9
 -2755.9   158.2 -2725.9   158.1 -2695.9     157 -2665.9   156.3 -2585.9   155.1
 -2485.9   156.8 -2265.9   156.4 -2245.9     157 -2195.9   156.4 -2015.9   155.7
 -1985.9   154.2 -1975.9     154 -1915.9   156.2 -1805.9   155.2 -1785.9   154.7
 -1765.9   155.4 -1755.9   154.5 -1735.9   155.4 -1725.9   154.7 -1715.9   154.7
 -1705.9   155.2 -1685.9   154.9 -1675.9   155.6 -1665.9   155.1 -1625.9   155.7
 -1605.9   155.7 -1575.9   155.1 -1565.9   154.6 -1535.9     154 -1505.9   154.3
 -1495.9   153.9 -1475.9   155.2 -1445.9     154 -1435.9   153.9 -1425.9   154.4
 -1325.9   153.5 -1265.9   153.3 -1125.9   153.3 -1105.9   152.7 -1085.9   153.7
  -815.9   152.8  -795.9     153  -765.9   151.6  -725.9   153.7  -695.9   153.6
  -665.9   151.7  -615.9   152.4  -185.9   151.5   -95.9   151.4   -85.9   151.1
    84.1   151.5   584.1   151.6   844.1   151.4  1741.9   151.4  1744.1   151.4
  1754.1     151  1774.1   151.7  1784.1   152.7  1794.1   153.2  1904.1   152.8
  1944.1   151.8  1974.1   151.8  2004.1   153.2  2214.1   153.4  2224.1   153.1
  2254.1   151.1  2274.1   150.9  2354.1   152.5  2414.1   152.7  2444.1   150.8
  2894.1   150.6  2924.1   149.8  2927.8  149.95  2934.1   150.2  2944.1     151
  3024.1   151.3  3094.1   149.6  3114.1   150.8  3204.1   151.8  3214.1   151.6
  3234.1   151.8  3334.1   151.5  3364.1   151.8  3394.1   151.3  3414.1   151.3
  3454.1   150.3  3534.1   151.3  3584.1   152.1  3604.1   151.9  3634.1   152.5
  3764.1   151.2  3784.1   151.6  3928.5  151.74  3994.1   151.8  4044.1   152.2
  4114.1   153.6  4154.1   152.8  4168.2  152.59  4254.1   151.3  4304.1   153.5
  4494.1   152.7  4564.1   151.6  4594.1   150.4  4753.2  152.39    4775  152.66
  4824.8  152.88  4825.3  152.88  4875.7   153.1  4919.2  153.29    4921  153.26
  4942.6  152.96 4944.79  152.39  4944.9  152.36 4945.01  152.33  4954.7  149.79
 4954.81  149.76  4954.9  149.74  4955.7  149.53  4972.7  144.18  4984.3  142.99
  4984.4  142.95  4985.1  142.77  4991.2  141.22  4998.8  140.82  5005.5   140.9
  5008.8  141.24  5014.5  142.11  5015.1  142.22  5026.5  144.23  5043.9     150
 5044.69  150.21  5044.8  150.24  5044.9  150.26 5054.79  152.86  5054.9  152.89
 5055.01  152.92  5058.2  153.76  5094.8  153.59  5102.4  153.56  5144.1  153.02
  5196.6  152.33  5246.6  151.68  5500.3   151.1  5530.3   150.4  5550.3   150.1
  5560.3   150.4  5570.3     150  5618.7  150.36  5650.3   150.6  5720.3   149.9
  5760.3   151.6  5790.3     152  5800.3   152.4  5840.3   153.1  5850.3   152.9
  5950.3   152.9  6100.3   152.5  6190.3   151.5  6270.3   152.1  6380.3   151.2
  6720.3   151.2  6740.3   152.7  6750.3   153.2  6760.3   153.2  6780.3   151.2
  6790.3   149.7  6800.3   149.1  6830.3   149.7  6850.3   149.7  6860.3   150.3
  6880.3   152.8  6900.3     154  6950.3     155  7006.9     154
BR U #Mann= 3
 -4395.9     .99  4942.6     .04  5058.2     .99
BR U Banks=4942.6,5058.2
BR D #Sta/Elev= 194
 -4395.9   166.6 -4305.9   166.6 -4295.9   165.9 -4095.9   164.7 -3775.9   160.9
 -3635.9   160.6 -3595.9   159.5 -3475.9   158.1 -3465.9   158.5 -3415.9   158.6
 -3365.9   160.2 -3295.9   160.1 -3285.9   160.5 -3185.9   160.3 -3095.9   156.5
 -3015.9   158.4 -3005.9   159.1 -2915.9   159.7 -2895.9   159.2 -2785.9   157.9
 -2755.9   158.2 -2725.9   158.1 -2695.9     157 -2665.9   156.3 -2585.9   155.1
 -2485.9   156.8 -2265.9   156.4 -2245.9     157 -2195.9   156.4 -2015.9   155.7
 -1985.9   154.2 -1975.9     154 -1915.9   156.2 -1805.9   155.2 -1785.9   154.7
 -1765.9   155.4 -1755.9   154.5 -1735.9   155.4 -1725.9   154.7 -1715.9   154.7
 -1705.9   155.2 -1685.9   154.9 -1675.9   155.6 -1665.9   155.1 -1625.9   155.7
 -1605.9   155.7 -1575.9   155.1 -1565.9   154.6 -1535.9     154 -1505.9   154.3
 -1495.9   153.9 -1475.9   155.2 -1445.9     154 -1435.9   153.9 -1425.9   154.4
 -1325.9   153.5 -1265.9   153.3 -1125.9   153.3 -1105.9   152.7 -1085.9   153.7
  -815.9   152.8  -795.9     153  -765.9   151.6  -725.9   153.7  -695.9   153.6
  -665.9   151.7  -615.9   152.4  -185.9   151.5   -95.9   151.4   -85.9   151.1
    84.1   151.5   584.1   151.6   844.1   151.4  1741.9   151.4  1744.1   151.4
  1754.1     151  1774.1   151.7  1784.1   152.7  1794.1   153.2  1904.1   152.8
  1944.1   151.8  1974.1   151.8  2004.1   153.2  2214.1   153.4  2224.1   153.1
  2254.1   151.1  2274.1   150.9  2354.1   152.5  2414.1   152.7  2444.1   150.8
  2894.1   150.6  2924.1   149.8  2927.8  149.95  2934.1   150.2  2944.1     151
  3024.1   151.3  3094.1   149.6  3114.1   150.8  3204.1   151.8  3214.1   151.6
  3234.1   151.8  3334.1   151.5  3364.1   151.8  3394.1   151.3  3414.1   151.3
  3454.1   150.3  3534.1   151.3  3584.1   152.1  3604.1   151.9  3634.1   152.5
  3764.1   151.2  3784.1   151.6  3928.5  151.74  3994.1   151.8  4044.1   152.2
  4114.1   153.6  4154.1   152.8  4168.2  152.59  4254.1   151.3  4304.1   153.5
  4494.1   152.7  4564.1   151.6  4594.1   150.4  4753.2  152.39    4775  152.66
  4824.8  152.88  4825.3  152.88  4875.7   153.1  4919.2  153.29    4921  153.26
  4942.6  152.96 4944.79  152.93  4944.9   152.9 4945.01  152.87  4954.7  150.33
 4954.81   150.3  4954.9  150.28  4955.7  150.07  4972.7  144.72  4984.3  143.53
  4984.4  143.49  4985.1  143.31  4991.2  141.76  4998.8  141.36  5005.5  141.44
  5008.8  141.78  5014.5  142.65  5015.1  142.76  5026.5  144.77  5043.9  150.54
 5044.69  150.75  5044.8  150.78  5044.9   150.8 5054.79   153.4  5054.9  153.43
 5055.01  153.46  5058.2  153.76  5094.8  153.59  5102.4  153.56  5144.1  153.02
  5196.6  152.33  5246.6  151.68  5500.3   151.1  5530.3   150.4  5550.3   150.1
  5560.3   150.4  5570.3     150  5618.7  150.36  5650.3   150.6  5720.3   149.9
  5760.3   151.6  5790.3     152  5800.3   152.4  5840.3   153.1  5850.3   152.9
  5950.3   152.9  6100.3   152.5  6190.3   151.5  6270.3   152.1  6380.3   151.2
  6720.3   151.2  6740.3   152.7  6750.3   153.2  6760.3   153.2  6780.3   151.2
  6790.3   149.7  6800.3   149.1  6830.3   149.7  6850.3   149.7  6860.3   150.3
  6880.3   152.8  6900.3     154  6950.3     155  7006.9     154
BR D #Mann= 3
 -4395.9     .99  4942.6     .04  5058.2     .99
BR D Banks=4942.6,5058.2
BC Design=,, 0 ,, 0 ,,,,,,
BC HTab HWMax=166.6

Type RM Length L Ch R = 1 ,17306   ,97.85,100,102.3
BEGIN DESCRIPTION:
S8_CYPRESS CHASE DR-DS - XS2
END DESCRIPTION:
XS GIS Cut Line= 4
      3014564.41      13926787.2      3010745.99     13919098.01
      3010699.59     13918997.01       3009771.9     13917285.01
#Sta/Elev= 30
 -3635.9   160.6 -3475.9   158.1 -3185.9   160.3 -3095.9   156.5 -2915.9   159.7
 -2585.9   155.1 -2245.9     157 -1975.9     154 -1605.9   155.7  -765.9   151.6
  -725.9   153.7  1754.1     151  2214.1   153.4  2274.1   150.9  2414.1   152.7
  3094.1   149.6  4114.1   153.6  4594.1   150.4  4942.6  152.96  4972.7  144.69
  4998.8  141.33  5026.5  144.74  5058.2  153.76  5720.3   149.9  5840.3   153.1
  6720.3   151.2  6760.3   153.2  6800.3   149.1  6900.3     154  7006.9     154
#Mann= 3 ,-1 , 0
 -3635.9     .99       0  4942.6     .04       0  5058.2     .99       0
Levee=0,,,-1,5217,151.1,,
#XS Ineff= 2 , 0
       0    4944   151.6    5054       0   151.6
Permanent Ineff=
       F       F
#Block Obstruct= 1 ,-1
 2424.71    3650   151.3
Bank Sta=4942.6,5058.2
XS Rating Curve= 0
Exp/Cntr=.5,.3

Type RM Length L Ch R = 1 ,17206   ,598.84,612,626.1
BEGIN DESCRIPTION:
S8_CYPRESS CHASE DR-DS - XS1
END DESCRIPTION:
XS GIS Cut Line= 4
      3014571.77      13926776.5      3010839.12     13919056.42
      3010792.71     13918955.42      3009865.03     13917243.42
#Sta/Elev= 30
 -3624.5  160.13 -3474.5  158.35 -3244.5  160.52 -3124.5  156.15 -2944.5  159.28
   -54.5  151.05  1715.5  153.26  1885.5  151.17  2125.5  153.28  2325.5  151.04
  2675.5  153.52  3035.5  150.09  3615.5  152.56  3835.5  149.12  4115.5  154.69
  4265.5  149.39  4365.5  141.74  4575.5  152.12  4895.5   154.3  4925.5  153.76
 4998.71  141.01  5071.8  153.29  5111.8  153.73  5601.8  151.62  5711.8  148.22
  6001.8  151.82  6741.8  151.21  6841.8  148.64  6891.8  153.63  6951.8   154.8
#Mann= 3 ,-1 , 0
 -3624.5     .99       0  4895.5     .04       0  5111.8     .99       0
Levee=0,,,-1,5270.25,151.36,,
#XS Ineff= 2 , 0
       0    4844   151.6    5154       0   151.6
Permanent Ineff=
       F       F
#Block Obstruct= 1 ,-1
 4209.78 4556.96   151.3
Bank Sta=4925.5,5071.8
XS Rating Curve= 0
Exp/Cntr=.3,.1

Type RM Length L Ch R = 1 ,16594   ,156.56,160,163.69
BEGIN DESCRIPTION:
Added channel cross section
END DESCRIPTION:
XS GIS Cut Line= 6
   3014529.8757613926747.9720319 3011659.114254913920333.7092272
 3011410.466425113918924.0259067 3011399.236122213918817.8023354
 3011387.096091613918767.7962657 3010896.175614613916940.1454147
#Sta/Elev= 30
-3588.18  159.85-3176.84  157.58-2910.72  159.14-2631.76   156.7-1994.14  157.03
-1641.81   154.2   63.76  150.66 2688.36  153.31 3047.02  151.02 3624.86  152.44
 3872.72  149.75 4083.41  152.66  4390.1   152.8  4510.1   150.9 4680.91  153.75
  4940.6  152.61  4998.1  137.94    5024  143.11  5053.3  151.98  5097.7   150.7
  5131.3  154.35 5302.72  150.54 5370.83  152.63 5516.78  151.88 5697.18  148.25
 6223.85  151.63 6616.34  149.83 6801.22  150.88 6849.87  148.74 6998.36  153.94
#Mann= 4 ,-1 , 0
-3588.18     .99       0  4940.6     .04       0  5053.3     .99       0
 6998.36     .99       0
Levee=0,,,-1,5228.517,150.7947,,
Bank Sta=4940.6,5053.3
XS Rating Curve= 0
Exp/Cntr=.3,.1

Type RM Length L Ch R = 1 ,16434   ,420.75,430,439.91
BEGIN DESCRIPTION:
Added channel cross section
END DESCRIPTION:
XS GIS Cut Line= 6
 3014526.121443713926738.3276806 3011709.304654213920316.4304289
  3011557.17453913918882.5165983 3011554.655830313918774.5025719
 3011545.296698813918723.6843108 3011160.641107413916861.7227283
#Sta/Elev= 30
 -3579.1  159.78 -3278.4  159.84-3168.14   157.1-2987.72  159.47-2623.57  156.66
-2005.42  157.05-1634.55  154.11   69.43   150.5 2691.57  153.26 3186.72  150.88
  3627.2  152.41 3874.83  149.88 4025.18   152.3  4510.1   150.9 4656.66  153.56
 4885.29  151.42  4938.6  153.09  4971.8  142.81    4998  138.38    5040   143.1
  5073.6  151.48    5132  153.97 5300.94  149.67 5369.59  152.42 5698.53  148.22
 5997.27   148.7 6166.91  151.59  6811.3  150.83 6860.34   148.7    7010  153.73
#Mann= 4 ,-1 , 0
 -3579.1     .99       0  4938.6     .04       0  5073.6     .99       0
    7010     .99       0
Levee=0,,,-1,5192,150.3,,
Bank Sta=4938.6,5073.6
XS Rating Curve= 0
Exp/Cntr=.3,.1

Type RM Length L Ch R = 1 ,16004   ,737.64,750,759.89
BEGIN DESCRIPTION:
Cross Section K145-00-00-X6 (updated with channel survey for Cypress Rosehill)
END DESCRIPTION:
XS GIS Cut Line= 5
 3014544.790142313926702.8499407        3011850.     13920235.35
      3011945.88     13918754.75       3011966.2     13918643.89
        3011850.     13916654.62
#Sta/Elev= 30
 -3556.4   159.6 -3256.4   159.9 -3156.4   155.9 -2966.4   159.9 -1566.4   153.7
  -236.4   153.4    83.6   150.1  2743.6   153.3  3193.6   150.2  3343.6   153.1
  3470.1   150.3  4030.1   152.1  4140.1   149.5  4250.1   152.7  4861.9   152.7
  4888.2  149.98  4933.9  152.84  4954.2   144.5  4997.6  137.72  5068.9  150.93
  5105.7  149.41  5128.6  153.07  5296.5   147.5  5366.5   151.9  5516.5   151.5
  5586.5   147.4  6006.5   147.2  6116.5   151.6  6886.5   148.6  7039.1   153.2
#Mann= 3 ,-1 , 0
 -3556.4     .99       0  4933.9     .04       0  5068.9     .99       0
Levee=0,,,-1,5192,150.3,,
Bank Sta=4933.9,5068.9
XS Rating Curve= 0
Exp/Cntr=.3,.1

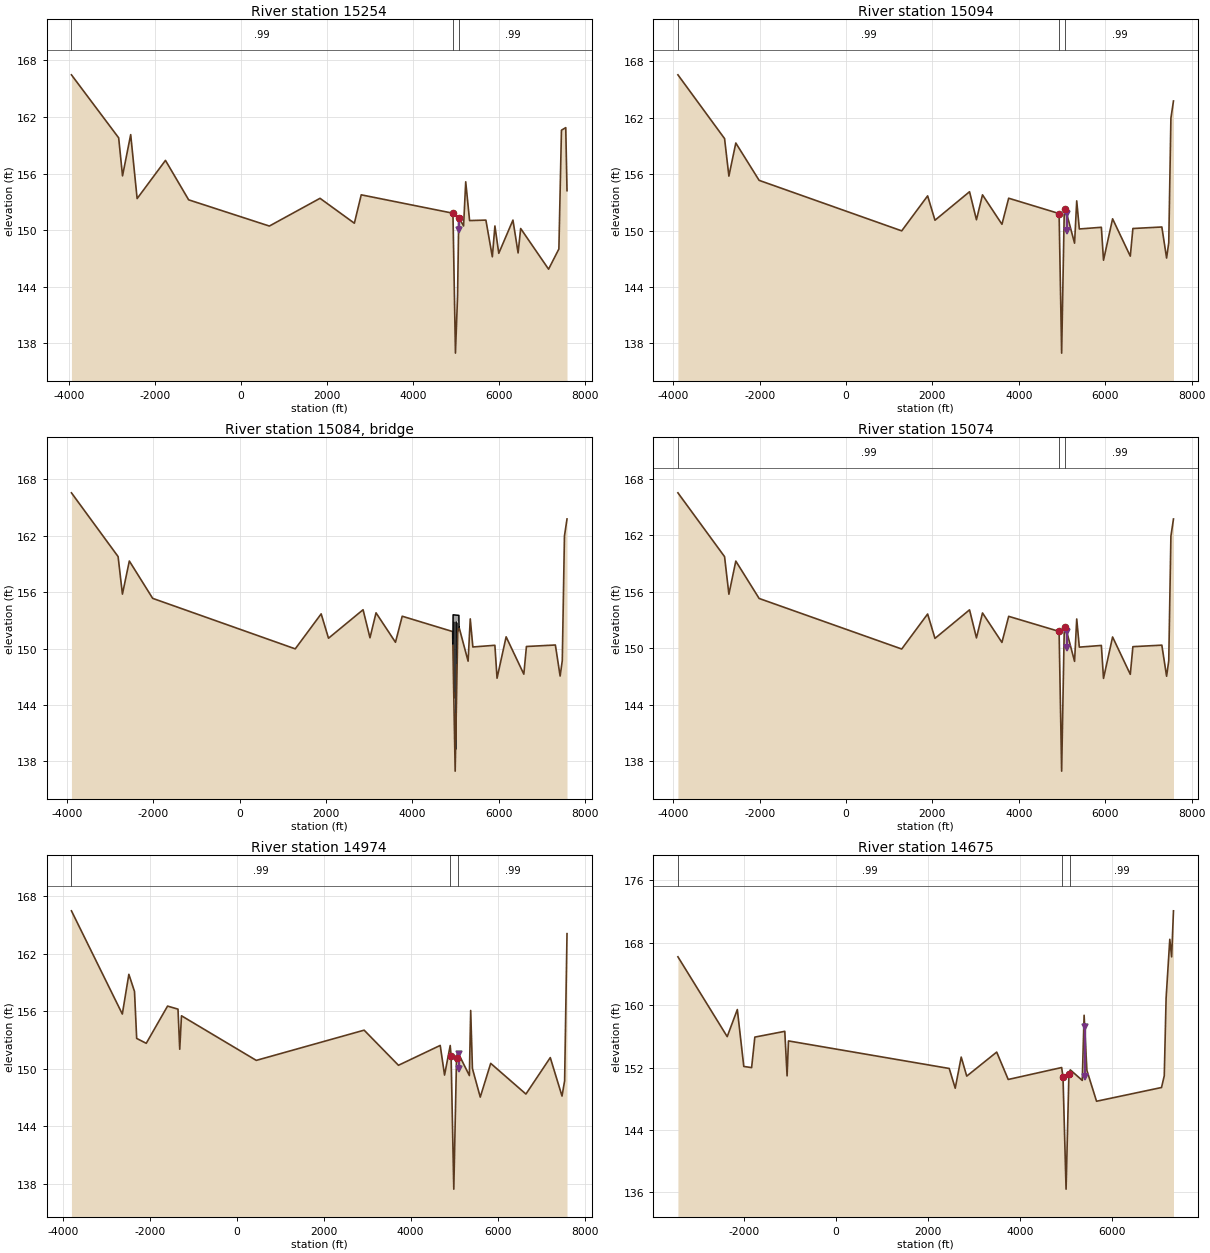
Type RM Length L Ch R = 1 ,15254   ,157.37,160,162.11
BEGIN DESCRIPTION:
Added channel cross section
END DESCRIPTION:
XS GIS Cut Line= 5
      3014867.12      13927450.1      3012300.57     13920308.77
      3012670.71     13919059.05      3012722.39       13918949.
       3012508.9     13916428.56
#Sta/Elev= 30
 -3952.3  166.46 -2852.3  159.78 -2762.3  155.75 -2572.3  160.12 -2422.3  153.34
 -1762.3  157.39 -1222.3  153.21   657.7  150.43  1837.7  153.37  2637.7  150.73
  2797.7  153.74    4934  151.79  4992.1  136.96  5041.3     143    5069  151.33
  5181.3  150.44  5231.3  155.12  5321.3  151.01  5701.3  151.06  5851.3  147.17
  5911.3  150.44  6001.3  147.54  6331.3  151.06  6451.3  147.58  6511.3  150.17
  7161.3  145.86  7401.3     148  7461.3  160.59  7561.3  160.86  7590.7  154.18
#Mann= 3 ,-1 , 0
 -3952.3     .99       0    4934     .04       0    5069     .99       0
Levee=0,,,-1,5084.12,150.02,,
Bank Sta=4934,5069
XS Rating Curve= 0
Exp/Cntr=.5,.3

Type RM Length L Ch R = 1 ,15094   ,20,20,20
BEGIN DESCRIPTION:
S5-1_PL-US - XS3 (updated with channel survey)
END DESCRIPTION:
XS GIS Cut Line= 5
      3014903.99     13927445.67      3012390.96     13920362.33
      3012761.11     13919112.62      3012812.78     13919002.57
       3012599.3     13916482.13
#Sta/Elev= 30
 -3890.8  166.56 -2810.8  159.78 -2710.8  155.79 -2550.8  159.31 -2010.8  155.34
  1289.2  149.97  1889.2  153.69  2059.2   151.1  2859.2  154.13  3019.2  151.15
  3159.2   153.8  3609.2  150.67  3765.1  153.44    4932  151.81    4991  136.97
    5050  151.69  5079.6  152.28  5290.1  148.66  5340.1  153.16  5400.1  150.17
  5910.1  150.35  5960.1  146.85  6170.1  151.25  6580.1  147.28  6640.1  150.22
  7310.1  150.38  7420.1  147.08  7470.1  148.72  7520.1  161.96  7579.5  163.78
#Mann= 3 ,-1 , 0
 -3890.8     .99       0    4932     .04       0  5079.6     .99       0
Levee=0,,,-1,5110,150,,
#XS Ineff= 2 , 0
       0    4932  146.86  5079.6       0  146.86
Permanent Ineff=
       F       F
Bank Sta=4932,5079.6
XS Rating Curve= 0
Exp/Cntr=.5,.3

Type RM Length L Ch R = 3 ,15084   ,,,
BEGIN DESCRIPTION:
PL1_K145-00-00-S5-1
END DESCRIPTION:
Bridge Culvert--1,0,-1,-1, 0
Deck Dist Width WeirC Skew NumUp NumDn MinLoCord MaxHiCord MaxSubmerge Is_Ogee
10,1,2.6,0, 9, 9, , , .95, 0, ,,,
  4938.2  4938.3 4938.41  4938.6  4942.6  5077.1 5079.39  5079.5  5079.6
  150.51  150.51  150.59  150.66  153.59  153.53  152.36  152.28  152.28
  150.51  150.48  150.44  150.41  152.92  152.86  152.27  152.27  152.28
  4938.2  4938.3 4938.41  4938.6  4942.6  5077.1 5079.39  5079.5  5079.6
  150.51  150.51  150.59  150.66  153.59  153.53  152.36  152.28  152.28
  150.51  150.48  150.44  150.41  152.92  152.86  152.27  152.27  152.28
Pier Skew, UpSta & Num, DnSta & Num=  ,4945.2, 2 ,4945.2, 2 , 0 , 0 , 0 ,,
     1.3     1.3
  147.05  153.92
     1.3     1.3
  147.05  153.92
Pier Skew, UpSta & Num, DnSta & Num=  ,4960.2, 2 ,4960.2, 2 , 0 , 0 , 0 ,,
     1.3     1.3
  142.92  153.91
     1.3     1.3
  142.92  153.91
Pier Skew, UpSta & Num, DnSta & Num=  ,4980.6, 2 ,4980.6, 2 , 0 , 0 , 0 ,,
     1.3     1.3
  136.91   153.9
     1.3     1.3
  136.91   153.9
Pier Skew, UpSta & Num, DnSta & Num=  ,5000.6, 2 ,5000.6, 2 , 0 , 0 , 0 ,,
     1.3     1.3
   138.6  153.89
     1.3     1.3
   138.6  153.89
Pier Skew, UpSta & Num, DnSta & Num=  ,5020.6, 2 ,5020.6, 2 , 0 , 0 , 0 ,,
     1.3     1.3
  142.68  153.89
     1.3     1.3
  142.68  153.89
Pier Skew, UpSta & Num, DnSta & Num=  ,5039.6, 2 ,5039.6, 2 , 0 , 0 , 0 ,,
     1.3     1.3
  147.92  153.88
     1.3     1.3
  147.92  153.88
BR Coef= 1 , 1 , 1 ,1.25, 0 ,,,.8,0,2,0,
WSPro=,,,, 1 ,,,, 0 ,,,, 0 ,,,,-1 ,-1 ,-1 , 0 , 0 , 0 , 0 , 0
BR U #Sta/Elev= 30
 -3890.8  166.56 -2810.8  159.78 -2710.8  155.79 -2550.8  159.31 -2010.8  155.34
  1289.2  149.97  1889.2  153.69  2059.2   151.1  2859.2  154.13  3019.2  151.15
  3159.2   153.8  3609.2  150.67  3765.1  153.44    4932  151.81    4991  136.97
    5050  151.69  5079.6  152.28  5290.1  148.66  5340.1  153.16  5400.1  150.17
  5910.1  150.35  5960.1  146.85  6170.1  151.25  6580.1  147.28  6640.1  150.22
  7310.1  150.38  7420.1  147.08  7470.1  148.72  7520.1  161.96  7579.5  163.78
BR U #Mann= 3
 -3890.8     .99    4932     .04  5079.6     .99
BR U Banks=4932,5079.6
BR D #Sta/Elev= 30
 -3890.8  166.53 -2810.8  159.75 -2710.8  155.76 -2550.8  159.28 -2010.8  155.31
  1289.2  149.94  1889.2  153.66  2059.2  151.07  2859.2   154.1  3019.2  151.12
  3159.2  153.77  3609.2  150.64  3765.1  153.41    4932  151.81    4991  136.97
    5050  151.69  5079.6  152.28  5290.1  148.63  5340.1  153.13  5400.1  150.14
  5910.1  150.32  5960.1  146.82  6170.1  151.22  6580.1  147.25  6640.1  150.19
  7310.1  150.35  7420.1  147.05  7470.1  148.69  7520.1  161.93  7579.5  163.75
BR D #Mann= 3
 -3890.8     .99    4932     .04  5079.6     .99
BR D Banks=4932,5079.6
BC Design=,, 0 ,, 0 ,,,,,,
BC HTab HWMax=166.56

Type RM Length L Ch R = 1 ,15074   ,104.81,100,96.39
BEGIN DESCRIPTION:
S5-1_PL-DS - XS2 (updated with channel survey)
END DESCRIPTION:
XS GIS Cut Line= 5
      3014922.83     13927438.98      3012411.99     13920361.78
      3012779.85     13919119.75      3012833.16     13919006.22
      3012619.23     13916480.44
#Sta/Elev= 30
 -3890.8  166.53 -2810.8  159.75 -2710.8  155.76 -2550.8  159.28 -2010.8  155.31
  1289.2  149.94  1889.2  153.66  2059.2  151.07  2859.2   154.1  3019.2  151.12
  3159.2  153.77  3609.2  150.64  3765.1  153.41    4932  151.81    4991  136.97
    5050  151.69  5079.6  152.28  5290.1  148.63  5340.1  153.13  5400.1  150.14
  5910.1  150.32  5960.1  146.82  6170.1  151.22  6580.1  147.25  6640.1  150.19
  7310.1  150.35  7420.1  147.05  7470.1  148.69  7520.1  161.93  7579.5  163.75
#Mann= 3 ,-1 , 0
 -3890.8     .99       0    4932     .04       0  5079.6     .99       0
Levee=0,,,-1,5110,150,,
#XS Ineff= 2 , 0
       0    4932  146.86  5079.6       0  146.86
Permanent Ineff=
       F       F
Bank Sta=4932,5079.6
XS Rating Curve= 0
Exp/Cntr=.5,.3

Type RM Length L Ch R = 1 ,14974   ,313.38,299,288.22
BEGIN DESCRIPTION:
S5-1_PL-DS - XS1 (updated with channel survey)
END DESCRIPTION:
XS GIS Cut Line= 5
       3014925.2      13927437.5      3012507.96     13920401.95
      3012875.83     13919159.92      3012929.14     13919046.39
       3012715.2     13916520.61
#Sta/Elev= 30
 -3798.6  166.47 -2628.6  155.71 -2478.6  159.85 -2348.6  158.07 -2298.6  153.17
 -2078.6  152.66 -1588.6  156.54 -1348.6  156.22 -1308.6  152.04 -1268.6  155.53
   451.4  150.88  2931.4  154.03  3720.6  150.37  4680.6  152.44  4780.6  149.35
  4910.6  152.43  4930.6  151.36 4992.93  137.46    5056  151.11  5081.4  151.75
  5351.4   149.3  5381.4  156.08  5421.4  150.03  5601.4  147.05  5841.4  150.57
  6651.4  147.37  7211.4  151.17  7481.4  147.16  7541.4  148.76  7596.2  164.09
#Mann= 3 ,-1 , 0
 -3798.6     .99       0  4910.6     .04       0  5081.4     .99       0
Levee=0,,,-1,5106.92,150.01,,
Bank Sta=4930.6,5056
XS Rating Curve= 0
Exp/Cntr=.3,.1

Type RM Length L Ch R = 1 ,14675   ,104.81,100,96.39
BEGIN DESCRIPTION:
S5A_PL-DS - XS4 (updated with channel survey)
END DESCRIPTION:
XS GIS Cut Line= 5
      3014897.98      13927352.5      3013045.25     13921017.59
      3013184.38     13919263.56      3013186.13     13919145.59
      3013028.88     13916412.23
#Sta/Elev= 30
   -3429   166.2   -2359  155.97   -2139  159.44   -1999  152.15   -1829     152
   -1759  155.91   -1109  156.65   -1059  150.94   -1029  155.42    2461  151.89
    2591  149.36    2721  153.35    2841  150.91  3491.3  153.99  3741.3  150.48
  4901.3  152.01  4930.9  150.77 4997.31  136.43  5058.9  151.15  5088.9  151.71
  5348.9  150.36  5388.9  158.71  5448.9  151.65  5658.9  147.69  7068.9  149.45
  7128.9  150.95  7168.9  160.91  7248.9  168.44  7288.9  166.19  7328.9  172.09
#Mann= 3 ,-1 , 0
   -3429     .99       0  4901.3     .04       0  5088.9     .99       0
Levee=0,,,-1,5401.69,150.79,,
Bank Sta=4930.9,5058.9
XS Rating Curve= 0
Exp/Cntr=.5,.3