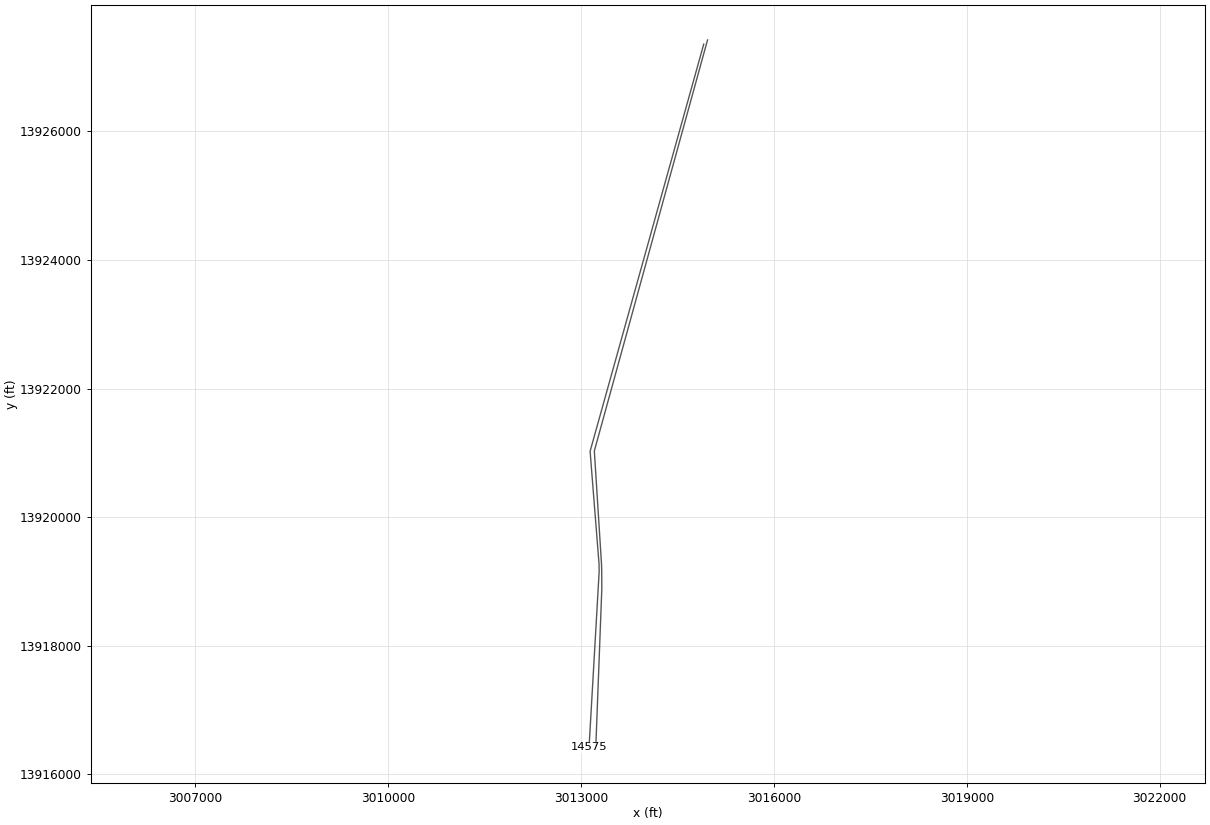
HEC-RAS study k145-00-00.prj: K145-00-00

--- k145-00-00.g01 (geometry) --- (continued)

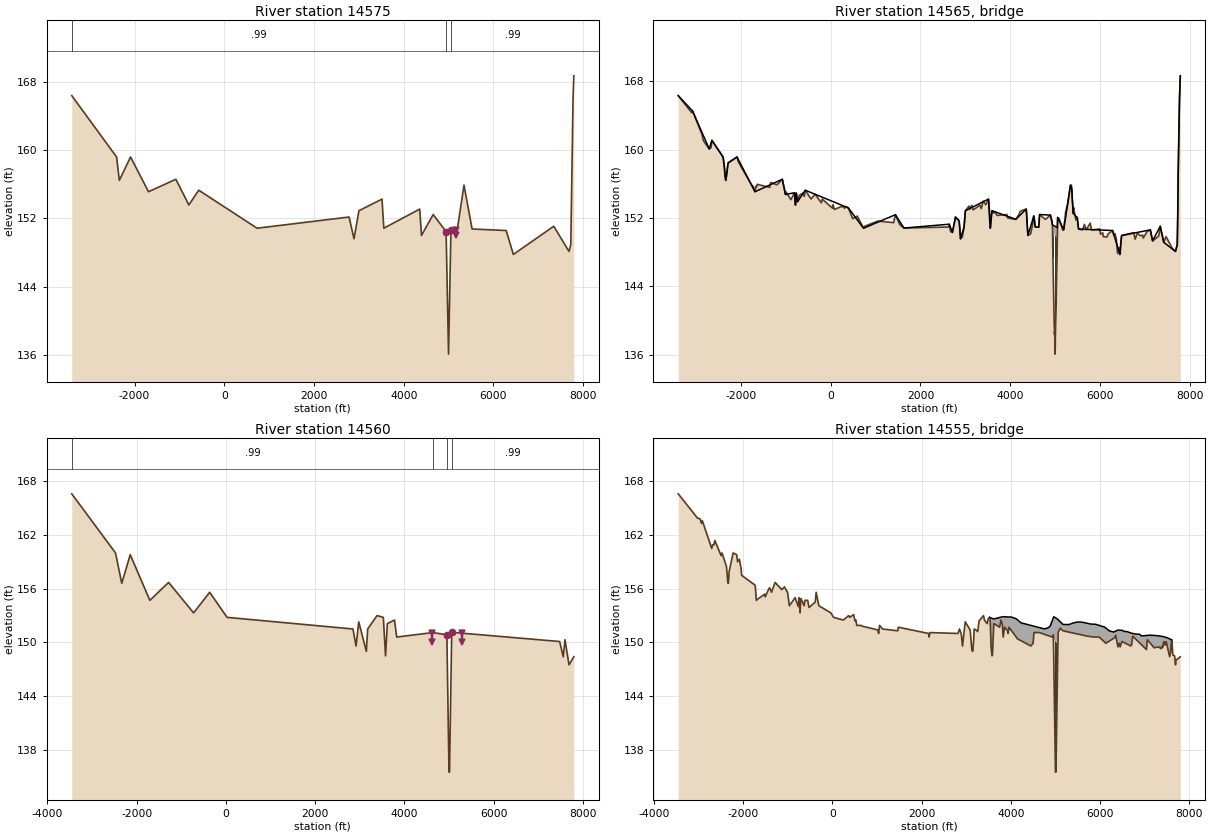
Type RM Length L Ch R = 1 ,14575   ,14,15,15
BEGIN DESCRIPTION:
S5A_PL-DS - XS3 (updated with channel survey)
END DESCRIPTION:
XS GIS Cut Line= 5
      3014908.18     13927357.75       3013140.7      13921025.6
      3013279.83     13919271.57      3013281.58     13919153.61
      3013124.32     13916420.25
#Sta/Elev= 30
 -3398.2  166.35 -2398.2  159.16 -2338.2  156.43 -2088.2  159.17 -1688.2   155.1
 -1078.2  156.56  -788.2  153.55  -568.2  155.28   731.8  150.83  2781.8  152.14
  2891.8  149.59  3001.8  152.88    3516  154.24    3556  150.83    4356  153.07
    4396  149.98    4656  152.43 4944.37  150.44 4998.77  136.09 5052.07  150.59
  5193.5  150.65  5343.5  155.88  5523.5  150.74  6283.5  150.56  6443.5  147.76
  7343.5  151.06  7683.5  148.11  7723.5  148.92  7773.5  166.01  7791.4  168.67
#Mann= 3 ,-1 , 0
 -3398.2     .99       0 4944.37     .04       0 5052.07     .99       0
Levee=0,,,-1,5174,150,,
#XS Ineff= 2 , 0
       0 4944.37  147.72 5052.07       0  147.72
Permanent Ineff=
       F       F
Bank Sta=4944.37,5052.07
XS Rating Curve= 0
Exp/Cntr=.5,.3

Type RM Length L Ch R = 3 ,14565   ,,,
BEGIN DESCRIPTION:
PL1_K145-00-00-S5A
END DESCRIPTION:
Bridge Culvert--1,0,-1,-1, 0
Deck Dist Width WeirC Skew NumUp NumDn MinLoCord MaxHiCord MaxSubmerge Is_Ogee
10,1,2.6,0, 60, 60, , , .95, 0, ,,,
 -3398.2 -3078.2 -2708.2 -2648.2 -2398.2 -2338.2 -2288.2 -2088.2 -1688.2 -1078.2
 -1008.2  -808.2  -788.2  -768.2  -738.2  -568.2   391.8   731.8  1441.8  1631.8
  2641.8  2711.8  2781.8  2861.8  2891.8  2971.8  3001.8    3516    3556    3596
    4126    4356    4396    4526    4556    4636    4656 4896.27 4944.97 5050.17
 5058.07  5193.5  5343.5  5373.5  5403.5  5493.5  5523.5  6283.5  6443.5  6483.5
  7123.5  7173.5  7343.5  7423.5  7683.5  7723.5  7733.5  7743.5  7773.5  7791.4
  166.31  164.51  160.07  161.08  159.12  156.39  158.42  159.13  155.06  156.52
  154.74  154.94  153.51  154.91   153.9  155.24  153.17  150.79  152.37  150.81
  151.26   150.3   152.1  151.65  149.55  150.92  152.84   154.2  150.79  152.84
  151.83  153.03  149.94  152.23  150.95  150.91  152.39  152.33  151.18  150.86
  152.05  150.61  155.84  155.37  152.53  152.05   150.7  150.52  147.72  149.93
   150.6   149.3  151.02  149.13  148.07  148.88  152.06  157.05  165.97  168.63
  166.31  164.51  160.07  161.08  159.12  156.39  158.42  159.13  155.06  156.52
  154.74  154.94  153.51  154.91   153.9  155.24  153.17  150.79  152.37  150.81
  151.26   150.3   152.1  151.65  149.55  150.92  152.84   154.2  150.79  152.84
  151.83  153.03  149.94  152.23  150.95  150.91  152.39  152.33  150.18  149.81
  152.05  150.61  155.84  155.37  152.53  152.05   150.7  150.52  147.72  149.93
   150.6   149.3  151.02  149.13  148.07  148.88  152.06  157.05  165.97  168.63
 -3398.2 -3078.2 -2708.2 -2648.2 -2398.2 -2338.2 -2288.2 -2088.2 -1688.2 -1078.2
 -1008.2  -808.2  -788.2  -768.2  -738.2  -568.2   391.8   731.8  1441.8  1631.8
  2641.8  2711.8  2781.8  2861.8  2891.8  2971.8  3001.8    3516    3556    3596
    4126    4356    4396    4526    4556    4636    4656 4896.27 4944.97 5050.17
 5058.07  5193.5  5343.5  5373.5  5403.5  5493.5  5523.5  6283.5  6443.5  6483.5
  7123.5  7173.5  7343.5  7423.5  7683.5  7723.5  7733.5  7743.5  7773.5  7791.4
  166.31  164.51  160.07  161.08  159.12  156.39  158.42  159.13  155.06  156.52
  154.74  154.94  153.51  154.91   153.9  155.24  153.17  150.79  152.37  150.81
  151.26   150.3   152.1  151.65  149.55  150.92  152.84   154.2  150.79  152.84
  151.83  153.03  149.94  152.23  150.95  150.91  152.39  152.33  151.18  150.86
  152.05  150.61  155.84  155.37  152.53  152.05   150.7  150.52  147.72  149.93
   150.6   149.3  151.02  149.13  148.07  148.88  152.06  157.05  165.97  168.63
  166.31  164.51  160.07  161.08  159.12  156.39  158.42  159.13  155.06  156.52
  154.74  154.94  153.51  154.91   153.9  155.24  153.17  150.79  152.37  150.81
  151.26   150.3   152.1  151.65  149.55  150.92  152.84   154.2  150.79  152.84
  151.83  153.03  149.94  152.23  150.95  150.91  152.39  152.33  150.18  149.81
  152.05  150.61  155.84  155.37  152.53  152.05   150.7  150.52  147.72  149.93
   150.6   149.3  151.02  149.13  148.07  148.88  152.06  157.05  165.97  168.63
Pier Skew, UpSta & Num, DnSta & Num=  ,4952, 2 ,4952, 2 , 0 , 0 , 0 ,,
     1.3     1.3
  146.14  151.16
     1.3     1.3
  146.14  151.16
Pier Skew, UpSta & Num, DnSta & Num=  ,4991.8, 2 ,4991.8, 2 , 0 , 0 , 0 ,,
     1.3     1.3
  137.41  151.04
     1.3     1.3
  137.41  151.04
Pier Skew, UpSta & Num, DnSta & Num=  ,5030.8, 2 ,5030.8, 2 , 0 , 0 , 0 ,,
     1.3     1.3
  142.81  150.92
     1.3     1.3
  142.81  150.92
BR Coef= 1 , 1 , 1 ,1.25, 0 ,,,.8,0,2,0,
WSPro=,,,, 1 ,,,, 0 ,,,, 0 ,,,,-1 ,-1 ,-1 , 0 , 0 , 0 , 0 , 0
BR U #Sta/Elev= 198
 -3398.2  166.31 -3098.2  164.31 -3078.2  164.51 -2868.2  161.78 -2838.2  161.05
 -2708.2  160.07 -2668.2   160.2 -2648.2  161.08 -2398.2  159.12 -2368.2     158
 -2358.2  156.77 -2338.2  156.39 -2318.2     157 -2288.2  158.42 -2088.2  159.13
 -2058.2  158.55 -1748.2  155.72 -1728.2  155.71 -1688.2  155.06 -1668.2   155.7
 -1648.2  155.64 -1638.2  155.93 -1358.2  155.57 -1338.2  156.14 -1198.2  155.87
 -1078.2  156.52 -1008.2  154.74  -998.2  155.05  -888.2  154.13  -808.2  154.94
  -798.2   154.6  -788.2  153.51  -778.2  153.54  -768.2  154.91  -758.2  154.77
  -748.2   154.1  -738.2   153.9  -698.2  154.65  -608.2  154.94  -588.2  154.51
  -568.2  155.24  -438.2  154.21  -348.2  154.77  -208.2  153.76  -188.2   154.2
    41.8  153.13    51.8  153.54    81.8  152.98   251.8  153.36   311.8  153.13
   331.8  153.33   391.8  153.17   491.8   151.9   591.8  152.21   731.8  150.79
   761.8  151.03  1051.8  151.63  1401.8  151.44  1441.8  152.37  1541.8  151.19
  1631.8  150.81  2631.8  150.93  2641.8  151.26  2671.8  150.39  2711.8   150.3
  2747.3  151.21  2781.8   152.1  2861.8  151.65  2881.8  150.69  2891.8  149.55
  2931.8  149.73  2971.8  150.92  3001.8  152.84  3081.8  153.38  3101.8  153.01
  3141.8  153.47    3176  152.94    3326  153.49    3356  153.08    3396  153.96
    3456  153.54    3516   154.2    3526  153.83    3536  152.93    3546  151.47
    3556  150.79  3558.3  150.87    3566  151.12    3576   152.3    3596  152.84
    3616   152.6    3676   152.6    3706  152.29    3926  152.39    3946  151.98
    4126  151.83    4186  152.31    4226  152.78    4356  153.03    4366  152.74
    4386  150.54    4396  149.94    4456  150.12    4506  151.38    4526  152.23
    4546  151.65    4556  150.95    4636  150.91    4656  152.39    4786  151.82
 4896.27  152.33 4929.97  151.61  4936.4   151.3 4939.27  151.17 4941.27  151.07
  4944.2  150.44 4944.37   150.4 4944.88  150.19 4944.97  150.16 4951.97  147.32
 4964.17  143.92 4980.17  139.83 4990.17  138.33 4991.77  138.74 4993.37  137.93
 4994.07  137.37 4998.77  136.05 5003.97  136.78 5006.57  138.09 5008.47  138.63
 5024.77  141.86 5030.77  144.05 5043.47  147.22 5050.06  149.77 5050.17  149.81
 5052.07  150.55 5054.27   151.1  5054.5  151.16 5058.07  152.05 5084.37  151.96
 5111.37  151.56  5173.5  150.55  5193.5  150.61  5203.5  151.32  5223.5  151.86
  5233.5  152.64  5283.5  153.68  5343.5  155.84  5363.5  155.82  5373.5  155.37
  5383.5  154.01  5393.5  153.53  5403.5  152.53  5413.5   153.2  5463.5  151.76
  5493.5  152.05  5523.5   150.7  5613.5  150.59  5653.5  151.24  5693.5  150.61
  5783.5  151.38  5813.5  150.56  5993.5  150.71  6013.5  150.09  6063.5  150.25
  6073.5  149.82  6153.5  149.75  6183.5  150.12  6283.5  150.52  6303.5  150.01
  6333.5  150.16  6363.5  149.57  6393.5  147.83  6423.5  148.54  6443.5  147.72
  6453.5   147.8  6463.5  149.07  6483.5  149.93  6753.5  150.27  6783.5  149.51
  6833.5   150.2  6903.5  149.91  6953.5  149.98  6963.5  149.64  7053.5   150.4
  7123.5   150.6  7173.5   149.3  7313.5  149.89  7343.5  151.02  7423.5  149.13
  7473.5   149.8  7613.5  148.43  7683.5  148.07  7723.5  148.88  7733.5  152.06
  7743.5  157.05  7773.5  165.97  7791.4  168.63
BR U #Mann= 3
 -3398.2     .99 4944.37     .04 5052.07     .99
BR U Banks=4944.37,5052.07
BR D #Sta/Elev= 198
 -3398.2  166.31 -3098.2  164.31 -3078.2  164.51 -2868.2  161.78 -2838.2  161.05
 -2708.2  160.07 -2668.2   160.2 -2648.2  161.08 -2398.2  159.12 -2368.2     158
 -2358.2  156.77 -2338.2  156.39 -2318.2     157 -2288.2  158.42 -2088.2  159.13
 -2058.2  158.55 -1748.2  155.72 -1728.2  155.71 -1688.2  155.06 -1668.2   155.7
 -1648.2  155.64 -1638.2  155.93 -1358.2  155.57 -1338.2  156.14 -1198.2  155.87
 -1078.2  156.52 -1008.2  154.74  -998.2  155.05  -888.2  154.13  -808.2  154.94
  -798.2   154.6  -788.2  153.51  -778.2  153.54  -768.2  154.91  -758.2  154.77
  -748.2   154.1  -738.2   153.9  -698.2  154.65  -608.2  154.94  -588.2  154.51
  -568.2  155.24  -438.2  154.21  -348.2  154.77  -208.2  153.76  -188.2   154.2
    41.8  153.13    51.8  153.54    81.8  152.98   251.8  153.36   311.8  153.13
   331.8  153.33   391.8  153.17   491.8   151.9   591.8  152.21   731.8  150.79
   761.8  151.03  1051.8  151.63  1401.8  151.44  1441.8  152.37  1541.8  151.19
  1631.8  150.81  2631.8  150.93  2641.8  151.26  2671.8  150.39  2711.8   150.3
  2747.3  151.21  2781.8   152.1  2861.8  151.65  2881.8  150.69  2891.8  149.55
  2931.8  149.73  2971.8  150.92  3001.8  152.84  3081.8  153.38  3101.8  153.01
  3141.8  153.47    3176  152.94    3326  153.49    3356  153.08    3396  153.96
    3456  153.54    3516   154.2    3526  153.83    3536  152.93    3546  151.47
    3556  150.79  3558.3  150.87    3566  151.12    3576   152.3    3596  152.84
    3616   152.6    3676   152.6    3706  152.29    3926  152.39    3946  151.98
    4126  151.83    4186  152.31    4226  152.78    4356  153.03    4366  152.74
    4386  150.54    4396  149.94    4456  150.12    4506  151.38    4526  152.23
    4546  151.65    4556  150.95    4636  150.91    4656  152.39    4786  151.82
 4896.27  152.33 4929.97  151.61  4936.4   151.3 4939.27  151.17 4941.27  151.07
  4944.2  150.44 4944.37   150.4 4944.88  150.19 4944.97  150.16 4951.97  147.32
 4964.17  143.92 4980.17  139.83 4990.17  138.33 4991.77  138.74 4993.37  137.93
 4994.07  137.37 4998.77  136.05 5003.97  136.78 5006.57  138.09 5008.47  138.63
 5024.77  141.86 5030.77  144.05 5043.47  147.22 5050.06  149.77 5050.17  149.81
 5052.07  150.55 5054.27   151.1  5054.5  151.16 5058.07  152.05 5084.37  151.96
 5111.37  151.56  5173.5  150.55  5193.5  150.61  5203.5  151.32  5223.5  151.86
  5233.5  152.64  5283.5  153.68  5343.5  155.84  5363.5  155.82  5373.5  155.37
  5383.5  154.01  5393.5  153.53  5403.5  152.53  5413.5   153.2  5463.5  151.76
  5493.5  152.05  5523.5   150.7  5613.5  150.59  5653.5  151.24  5693.5  150.61
  5783.5  151.38  5813.5  150.56  5993.5  150.71  6013.5  150.09  6063.5  150.25
  6073.5  149.82  6153.5  149.75  6183.5  150.12  6283.5  150.52  6303.5  150.01
  6333.5  150.16  6363.5  149.57  6393.5  147.83  6423.5  148.54  6443.5  147.72
  6453.5   147.8  6463.5  149.07  6483.5  149.93  6753.5  150.27  6783.5  149.51
  6833.5   150.2  6903.5  149.91  6953.5  149.98  6963.5  149.64  7053.5   150.4
  7123.5   150.6  7173.5   149.3  7313.5  149.89  7343.5  151.02  7423.5  149.13
  7473.5   149.8  7613.5  148.43  7683.5  148.07  7723.5  148.88  7733.5  152.06
  7743.5  157.05  7773.5  165.97  7791.4  168.63
BR D #Mann= 3
 -3398.2     .99 4944.37     .04 5052.07     .99
BR D Banks=4944.37,5052.07
BC Design=,, 0 ,, 0 ,,,,,,
BC HTab HWMax=168.67

Type RM Length L Ch R = 1 ,14560   ,104,105,106
BEGIN DESCRIPTION:
S5_CYPRESS ROSEHILL-DS - XS3  **SEE NOTE**
The right end of this XS stops under an overpass.  This XS cannot be extended to high ground.  This is a spill to the main stem of Cypress unless a levee is possible at sta 5700.
END DESCRIPTION:
XS GIS Cut Line= 6
      3014967.26     13927422.85      3013206.48     13921030.39
      3013318.18     13919271.48      3013321.45     13919155.81
      3013323.21     13918893.01      3013229.07     13916416.98
#Sta/Elev= 30
 -3452.5   166.6 -2472.5     160 -2332.5   156.6 -2142.5   159.8 -1702.5   154.7
 -1282.5   156.7  -722.5   153.3  -362.5   155.6    27.5   152.8  2847.5   151.5
  2917.5   149.6  2977.5   152.3  3147.5     149    3178   151.5    3388     153
    3528   152.8    3578   148.5    3618   152.1    3778   152.5    3828   150.6
    4638   151.1  4952.2  150.85  4999.4  135.51    5011  135.51  5060.6  151.13
    7479   150.1    7559   148.4    7599   150.3    7689   147.5  7796.8   148.4
#Mann= 4 ,-1 , 0
 -3452.5     .99       0    4638      .1       0  4952.2     .04       0
  5060.6     .99       0
Levee=-1,4626,150,-1,5282,150,,
#XS Ineff= 2 , 0
       0  4952.2   147.5  5060.6       0   147.5
Permanent Ineff=
       F       F
Bank Sta=4952.2,5060.6
XS Rating Curve= 0
Exp/Cntr=.5,.3

Type RM Length L Ch R = 3 ,14555   ,,,
BEGIN DESCRIPTION:
CYPRESS-ROSEHILL BRIDGE
Structure ID: K145-00-00-S5
END DESCRIPTION:
Bridge Culvert--1,0,-1,-1, 0
Deck Dist Width WeirC Skew NumUp NumDn MinLoCord MaxHiCord MaxSubmerge Is_Ogee
5,94,2.6,0, 40, 40, , , .95, 0, ,,,
    3528  3611.9  3717.9  3817.9  3917.9  4015.9  4120.9  4225.9  4752.9  4831.9
  4881.9  4960.9  5048.9  5081.9  5166.9  5294.9  5396.9  5497.9  5596.9  5699.9
  5791.9  5895.9  6102.9  6202.9  6301.9  6401.9  6502.9  6531.9  6602.9  6697.9
  6801.9  6889.9  6917.9  7013.9  7110.9  7208.9  7306.9  7407.9  7505.9    7599
   152.8  152.62  152.74  152.88  152.85  152.83  152.64  152.19  151.51  151.63
  151.83  152.87   152.6  152.43  152.01  151.99  152.17  152.29  152.26  152.15
  152.05  152.03  151.71   151.3  151.16  151.38  151.35  151.23  151.21  151.04
  150.93  150.91  150.73  150.76  150.81  150.78  150.74  150.66  150.52   150.3
                                                                                
          150.28  150.01
                                                                                
                                                                                
    3528  3611.9  3717.9  3817.9  3917.9  4015.9  4120.9  4225.9  4752.9  4831.9
  4881.9  4960.9  5048.9  5081.9  5166.9  5294.9  5396.9  5497.9  5596.9  5699.9
  5791.9  5895.9  6102.9  6202.9  6301.9  6401.9  6502.9  6531.9  6602.9  6697.9
  6801.9  6889.9  6917.9  7013.9  7110.9  7208.9  7306.9  7407.9  7505.9    7599
   152.8  152.62  152.74  152.88  152.85  152.83  152.64  152.19  151.51  151.63
  151.83  152.87   152.6  152.43  152.01  151.99  152.17  152.29  152.26  152.15
  152.05  152.03  151.71   151.3  151.16  151.38  151.35  151.23  151.21  151.04
  150.93  150.91  150.73  150.76  150.81  150.78  150.74  150.66  150.52   150.3
                                                                                
          150.28  150.01
                                                                                
                                                                                
Pier Skew, UpSta & Num, DnSta & Num=  ,4989.9, 2 ,4989.9, 2 , 0 , 0 , 0 ,,
    1.35    1.35
  137.17   151.8
    1.35    1.35
  137.17   151.8
Pier Skew, UpSta & Num, DnSta & Num=  ,5019.9, 2 ,5019.9, 2 , 0 , 0 , 0 ,,
    1.35    1.35
  137.16  151.86
    1.35    1.35
  137.16  151.86
BR Coef= 1 , 1 , 1 ,1.25, 0 ,,,.8,0,2,0,
WSPro=,,,, 1 ,,,, 0 ,,,, 0 ,,,,-1 ,-1 ,-1 , 0 , 0 , 0 , 0 , 0
BR U #Sta/Elev= 148
 -3452.5   166.6 -3022.5   163.9 -2962.5   163.8 -2932.5   163.3 -2912.5   163.6
 -2702.5   160.5 -2682.5   160.9 -2652.5   160.9 -2632.5   161.4 -2492.5   159.7
 -2472.5     160 -2372.5   158.5 -2342.5   156.8 -2332.5   156.6 -2322.5     157
 -2312.5   157.9 -2222.5     160 -2142.5   159.8 -2122.5     159 -2082.5   159.3
 -2042.5   158.2 -2032.5   157.5 -1732.5   156.4 -1722.5   156.1 -1702.5   154.7
 -1682.5   154.8 -1512.5   155.4 -1502.5   155.1 -1422.5     156 -1402.5   156.1
 -1362.5   155.6 -1282.5   156.7 -1132.5   155.9 -1072.5   156.2 -1002.5   155.6
  -962.5   154.1  -832.5     155  -762.5     154  -742.5     155  -722.5   153.3
  -712.5   154.4  -702.5   154.9  -632.5   154.1  -612.5   154.7  -552.5   154.7
  -522.5   153.9  -382.5   154.5  -362.5   155.6  -302.5   154.1   -32.5   153.3
    27.5   152.8   247.5   152.5   367.5     153   387.5   152.8   477.5   153.1
   507.5   152.4   527.5   152.5   547.5   151.9   647.5   151.9   677.5   151.8
  1017.5   151.4  1037.5     151  1057.5   151.9  1127.5   151.5  1467.5   151.3
  1477.5   151.7  2157.5     151  2167.5   150.6  2187.5   151.1  2817.5     151
  2847.5   151.5  2887.5     151  2917.5   149.6  2977.5   152.3  3087.5   151.4
  3127.5   149.1  3147.5     149  3167.5   150.3  3177.5   151.4    3178   151.5
    3218   151.4    3258   151.2    3288   152.4    3388     153    3408   152.5
    3468   152.1    3498   152.7    3528   152.8    3538   152.3    3558   149.4
    3578   148.5    3588   148.6    3618   152.1    3748   151.7    3778   152.5
    3808     152    3828   150.6    3858   151.7    3928   151.3    3938     151
    3958   151.7    4148   150.4    4448   149.6    4498   149.9    4518   151.1
    4638   151.1  4925.9   150.6  4952.2  150.85  4960.9  148.35  4999.4  135.51
    5011  135.51  5048.9  148.15  5060.6  151.13  5069.5  151.21  5106.2   151.6
  5166.2   151.3    5709   150.7    5859   150.6    5979   150.6    6129   149.9
    6319   150.5    6349   150.8    6399   149.5    6429   149.9    6449   149.5
    6489   150.1    6689   149.6    6709   149.8    6729   150.7    7039   149.2
    7059   150.3    7209   149.4    7319   149.5    7359   149.3    7389   149.6
    7399   149.4    7429   150.1    7459   149.7    7479   150.1    7559   148.4
    7579   148.9    7599   150.3    7609   150.2    7629   148.6    7669   148.5
    7689   147.5    7699     148  7796.8   148.4
BR U #Mann= 4
 -3452.5     .99    4638      .1  4952.2    .035  5060.6     .99
BR D #Sta/Elev= 148
 -3452.5   166.6 -3022.5   163.9 -2962.5   163.8 -2932.5   163.3 -2912.5   163.6
 -2702.5   160.5 -2682.5   160.9 -2652.5   160.9 -2632.5   161.4 -2492.5   159.7
 -2472.5     160 -2372.5   158.5 -2342.5   156.8 -2332.5   156.6 -2322.5     157
 -2312.5   157.9 -2222.5     160 -2142.5   159.8 -2122.5     159 -2082.5   159.3
 -2042.5   158.2 -2032.5   157.5 -1732.5   156.4 -1722.5   156.1 -1702.5   154.7
 -1682.5   154.8 -1512.5   155.4 -1502.5   155.1 -1422.5     156 -1402.5   156.1
 -1362.5   155.6 -1282.5   156.7 -1132.5   155.9 -1072.5   156.2 -1002.5   155.6
  -962.5   154.1  -832.5     155  -762.5     154  -742.5     155  -722.5   153.3
  -712.5   154.4  -702.5   154.9  -632.5   154.1  -612.5   154.7  -552.5   154.7
  -522.5   153.9  -382.5   154.5  -362.5   155.6  -302.5   154.1   -32.5   153.3
    27.5   152.8   247.5   152.5   367.5     153   387.5   152.8   477.5   153.1
   507.5   152.4   527.5   152.5   547.5   151.9   647.5   151.9   677.5   151.8
  1017.5   151.4  1037.5     151  1057.5   151.9  1127.5   151.5  1467.5   151.3
  1477.5   151.7  2157.5     151  2167.5   150.6  2187.5   151.1  2817.5     151
  2847.5   151.5  2887.5     151  2917.5   149.6  2977.5   152.3  3087.5   151.4
  3127.5   149.1  3147.5     149  3167.5   150.3  3177.5   151.4    3178   151.5
    3218   151.4    3258   151.2    3288   152.4    3388     153    3408   152.5
    3468   152.1    3498   152.7    3528   152.8    3538   152.3    3558   149.4
    3578   148.5    3588   148.6    3618   152.1    3748   151.7    3778   152.5
    3808     152    3828   150.6    3858   151.7    3928   151.3    3938     151
    3958   151.7    4148   150.4    4448   149.6    4498   149.9    4518   151.1
    4638   151.1  4925.9   150.6  4952.2  150.85  4960.9  148.35  4999.4  135.51
    5011  135.51  5048.9  148.15  5060.6  151.13  5069.5  151.21  5106.2   151.6
  5166.2   151.3    5709   150.7    5859   150.6    5979   150.6    6129   149.9
    6319   150.5    6349   150.8    6399   149.5    6429   149.9    6449   149.5
    6489   150.1    6689   149.6    6709   149.8    6729   150.7    7039   149.2
    7059   150.3    7209   149.4    7319   149.5    7359   149.3    7389   149.6
    7399   149.4    7429   150.1    7459   149.7    7479   150.1    7559   148.4
    7579   148.9    7599   150.3    7609   150.2    7629   148.6    7669   148.5
    7689   147.5    7699     148  7796.8   148.4
BR D #Mann= 4
 -3452.5     .99  2977.5      .1  4952.2    .035  5060.6     .99
BC Design=,, 0 ,, 0 ,,,,,,
BC HTab HWMax=166.72