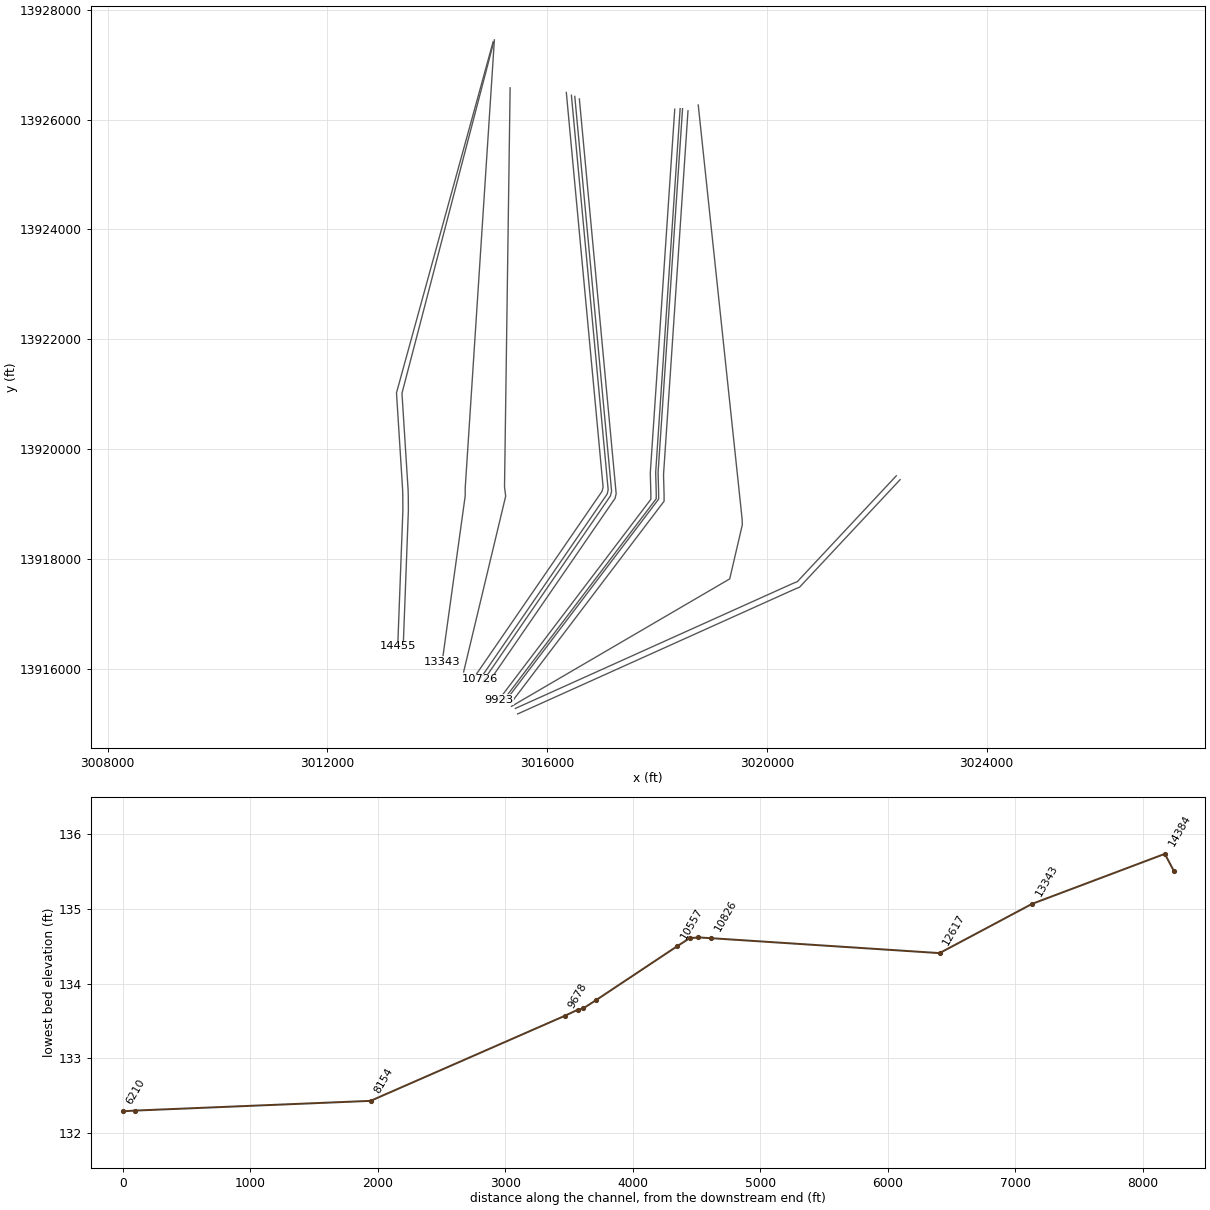
HEC-RAS study k145-00-00.prj: K145-00-00

--- k145-00-00.g01 (geometry) --- (continued)

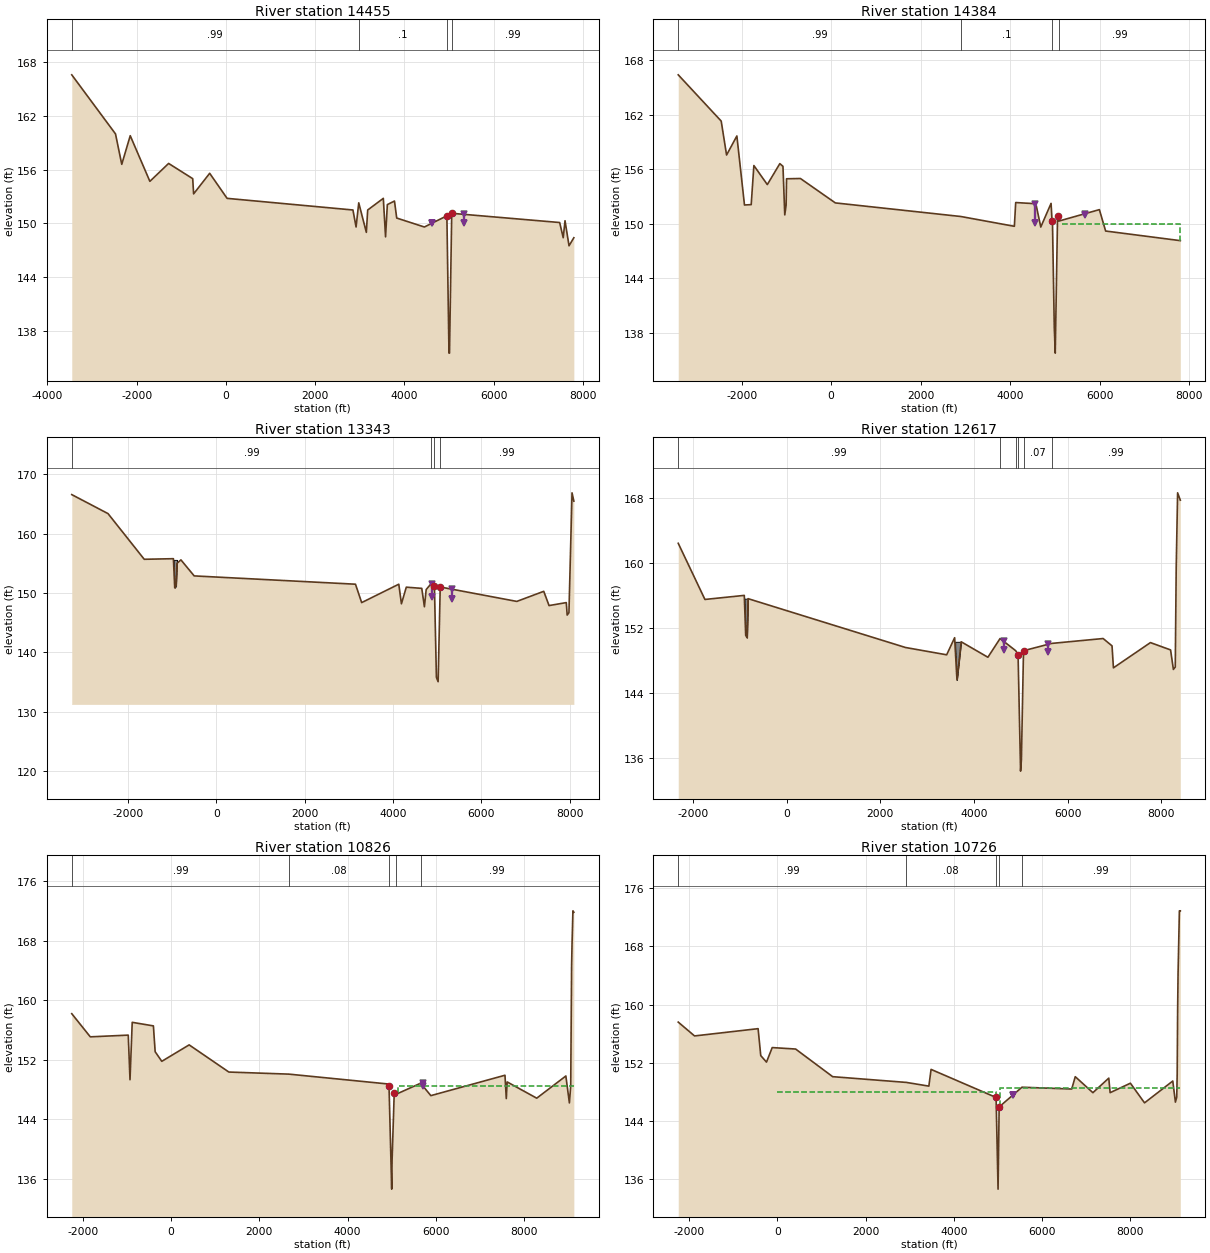
Type RM Length L Ch R = 1 ,14455   ,71,71,70.65
BEGIN DESCRIPTION:
S5_CYPRESS ROSEHILL-DS - XS2
END DESCRIPTION:
XS GIS Cut Line= 6
      3015017.93     13927417.11      3013258.04     13921027.88
      3013369.55     13919271.97      3013372.84     13919155.73
       3013374.6     13918892.27      3013280.45     13916415.79
#Sta/Elev= 30
 -3452.5   166.6 -2472.5     160 -2332.5   156.6 -2142.5   159.8 -1702.5   154.7
 -1282.5   156.7  -742.5     155  -722.5   153.3  -362.5   155.6    27.5   152.8
  2847.5   151.5  2917.5   149.6  2977.5   152.3  3147.5     149    3178   151.5
    3528   152.8    3578   148.5    3618   152.1    3778   152.5    3828   150.6
    4448   149.6  4952.2  150.85  4999.4  135.51    5011  135.51  5060.6  151.13
    7479   150.1    7559   148.4    7599   150.3    7689   147.5  7796.8   148.4
#Mann= 4 ,-1 , 0
 -3452.5     .99       0  2977.5      .1       0  4952.2     .04       0
  5060.6     .99       0
Levee=-1,4626,150,-1,5335,150,,
#XS Ineff= 2 , 0
       0  4952.2   147.5  5060.6       0   147.5
Permanent Ineff=
       F       F
Bank Sta=4952.2,5060.6
XS Rating Curve= 0
Exp/Cntr=.5,.3

Type RM Length L Ch R = 1 ,14384   ,1041,1041,1037.35
BEGIN DESCRIPTION:
S5_CYPRESS ROSEHILL-DS - XS1
END DESCRIPTION:
XS GIS Cut Line= 6
       3015026.4      13927405.6      3013357.86     13921020.59
      3013469.36     13919264.68      3013472.65     13919148.44
      3013474.42     13918884.98      3013380.26      13916408.5
#Sta/Elev= 30
 -3416.7  166.42 -2456.7  161.32 -2336.7  157.58 -2106.7  159.68 -1936.7  152.07
 -1786.7  152.11 -1726.7  156.42 -1426.7  154.32 -1146.7  156.63 -1076.7  156.33
 -1036.7  150.98 -1006.7  152.05  -996.7  154.96  -686.7  154.99    93.3   152.3
 2898.19   150.8  4092.8  149.72  4122.8  152.34  4572.8  152.21  4682.8  149.64
  4912.8  152.25  4932.8  150.49 4943.56  150.34  4984.6  138.57  5006.1  135.74
  5058.1  150.89  5088.5   150.3    5992  151.56    6132   149.2  7800.2  148.14
#Mann= 4 ,-1 , 0
 -3416.7     .99       0 2898.19      .1       0  4932.8     .04       0
  5088.5     .99       0
Levee=-1,4543.07,150.07,-1,5672.18,150.94,,
#XS Ineff= 2 , 0
       0    4844     150    5155       0     150
Permanent Ineff=
       F       F
Bank Sta=4943.56,5058.1
XS Rating Curve= 0
Exp/Cntr=.3,.1

Type RM Length L Ch R = 1 ,13343   ,716,726,730
BEGIN DESCRIPTION:
Cross Section K145-00-00-X5
END DESCRIPTION:
XS GIS Cut Line= 4
      3015040.11     13927448.89       3014509.3     13919300.47
       3014509.3     13919155.76      3014089.59     13916133.79
#Sta/Elev= 30
 -3271.5   166.6 -2451.5   163.4 -1631.5   155.7  -971.5   155.8  -941.5   150.9
  -911.5   151.2  -891.5     155  -801.5   155.6  -501.5   152.9  3148.5   151.5
  3288.5   148.4  4128.5   151.5  4188.5   148.2  4298.5     151  4648.5   150.8
  4708.5   147.7  4748.5   150.6  4863.9  151.62  4934.8  151.19  4980.1   135.8
  5018.6  135.07  5066.4  151.03  6798.9   148.6  7408.9   150.3  7528.9   147.9
  7918.9   148.4  7938.9   146.3  7978.9   146.7  8048.9   166.9  8089.9   165.5
#Mann= 4 ,-1 , 0
 -3271.5     .99       0  4863.9      .5       0  4934.8     .04       0
  5066.4     .99       0
Levee=-1,4874,149.3,-1,5338,149,,
#Block Obstruct= 2 ,-1
  -966.9  -891.4   155.6    -890    -889     120
Bank Sta=4934.8,5066.4
XS Rating Curve= 0
Exp/Cntr=.3,.1

Type RM Length L Ch R = 1 ,12617   ,1799.52,1791,1770.16
BEGIN DESCRIPTION:
Cross Section K145-00-00-X4
END DESCRIPTION:
XS GIS Cut Line= 4
      3015326.56      13926576.5      3015224.58     13919317.79
      3015245.72     13919148.69      3014480.21      13915951.5
#Sta/Elev= 30
 -2311.4   162.4 -1741.4   155.5  -901.4     156  -871.4   151.1  -841.4   150.8
  -821.4   155.6  2538.6   149.6  3418.6   148.7  3588.6   150.8  3638.6   145.6
  3728.6   150.3  4298.6   148.4  4558.6   150.7  4892.9   149.2  4935.7   148.8
  4942.8  148.73  4996.1  134.41  5013.6  135.75  5058.9   149.2  5658.4   150.1
  6758.4   150.7  6948.4   149.8  6978.4   147.1  7768.4   150.2  8198.4   149.3
  8258.4   146.9  8298.4   147.2  8318.4   159.4  8348.4   168.6    8406   167.7
#Mann= 6 ,-1 , 0
 -2311.4     .99       0  4558.6     .08       0  4892.9     .06       0
  4935.7     .04       0  5058.9     .07       0  5658.4     .99       0
Levee=-1,4635,149.3,-1,5575,149,,
#Block Obstruct= 2 ,-1
  -901.3  -821.6   155.6  3600.6  3728.5   150.3
Bank Sta=4942.8,5058.9
XS Rating Curve= 0
Exp/Cntr=.3,.1

Type RM Length L Ch R = 1 ,10826   ,100.48,100,98.84
BEGIN DESCRIPTION:
S5-2_SKINNER RD-US - XS4
END DESCRIPTION:
XS GIS Cut Line= 4
      3016349.49      13926492.8      3017019.12     13919315.78
        3017001.     13919238.46      3014682.82      13915867.8
#Sta/Elev= 30
 -2250.2  158.18 -1830.2  155.07  -970.2   155.3  -930.2  149.31  -880.2  157.02
  -400.2  156.54  -360.2  153.07  -210.2  151.78   409.8  153.99  1309.8  150.34
  2669.8  150.06  4929.8  148.73  4939.8  148.41 5000.36  134.61 5008.73  138.42
  5057.4   147.5  5087.4  147.32  5657.4  148.84  5887.4  147.17  7567.4  149.91
  7597.4  146.77  7617.4  149.01  8287.4  146.83  8947.4  149.81  9027.4  146.19
  9057.4  148.45  9077.4  164.54  9087.4  167.55  9107.4     172  9128.3  171.81
#Mann= 5 ,-1 , 0
 -2250.2     .99       0  2669.8     .08       0  4929.8     .04       0
  5087.4     .06       0  5657.4     .99       0
Levee=0,,,-1,5705.19,148.87,,
#XS Ineff= 2 , 0
       0    4846     148    5142       0   148.5
Permanent Ineff=
       F       F
Bank Sta=4939.8,5057.4
XS Rating Curve= 0
Exp/Cntr=.5,.3

Type RM Length L Ch R = 1 ,10726   ,68,69,71
BEGIN DESCRIPTION:
S5-2_SKINNER RD-US - XS3
END DESCRIPTION:
XS GIS Cut Line= 4
      3016441.93     13926441.99      3017111.56     13919264.97
      3017093.44     13919187.65      3014775.27     13915816.99
#Sta/Elev= 30
 -2247.6  157.58 -1877.6  155.68  -437.6  156.68  -377.6  152.98  -247.6  152.08
  -117.6  154.08   412.4  153.88  1252.4  150.08  2922.6  149.29  3432.4  148.78
  3482.4  151.08  4955.9  147.22  5000.6  134.62  5025.4  145.92  5542.2  148.63
    6670  148.38    6750  150.08    7150  147.88    7510  149.88    7540  147.88
    8000  149.18    8320  146.48    8960  149.48    9020  146.58    9050  147.28
    9060  150.38    9070  158.98    9080  164.28    9110  172.88  9130.9  172.88
#Mann= 5 ,-1 , 0
 -2247.6     .99       0  2922.6     .08       0  4955.9     .04       0
  5025.4     .06       0  5542.2     .99       0
Levee=0,,,-1,5338,147.6,,
#XS Ineff= 2 , 0
       0    4946     148    5042       0   148.5
Permanent Ineff=
       F       F
Bank Sta=4955.9,5025.4
XS Rating Curve= 0
Exp/Cntr=.5,.3

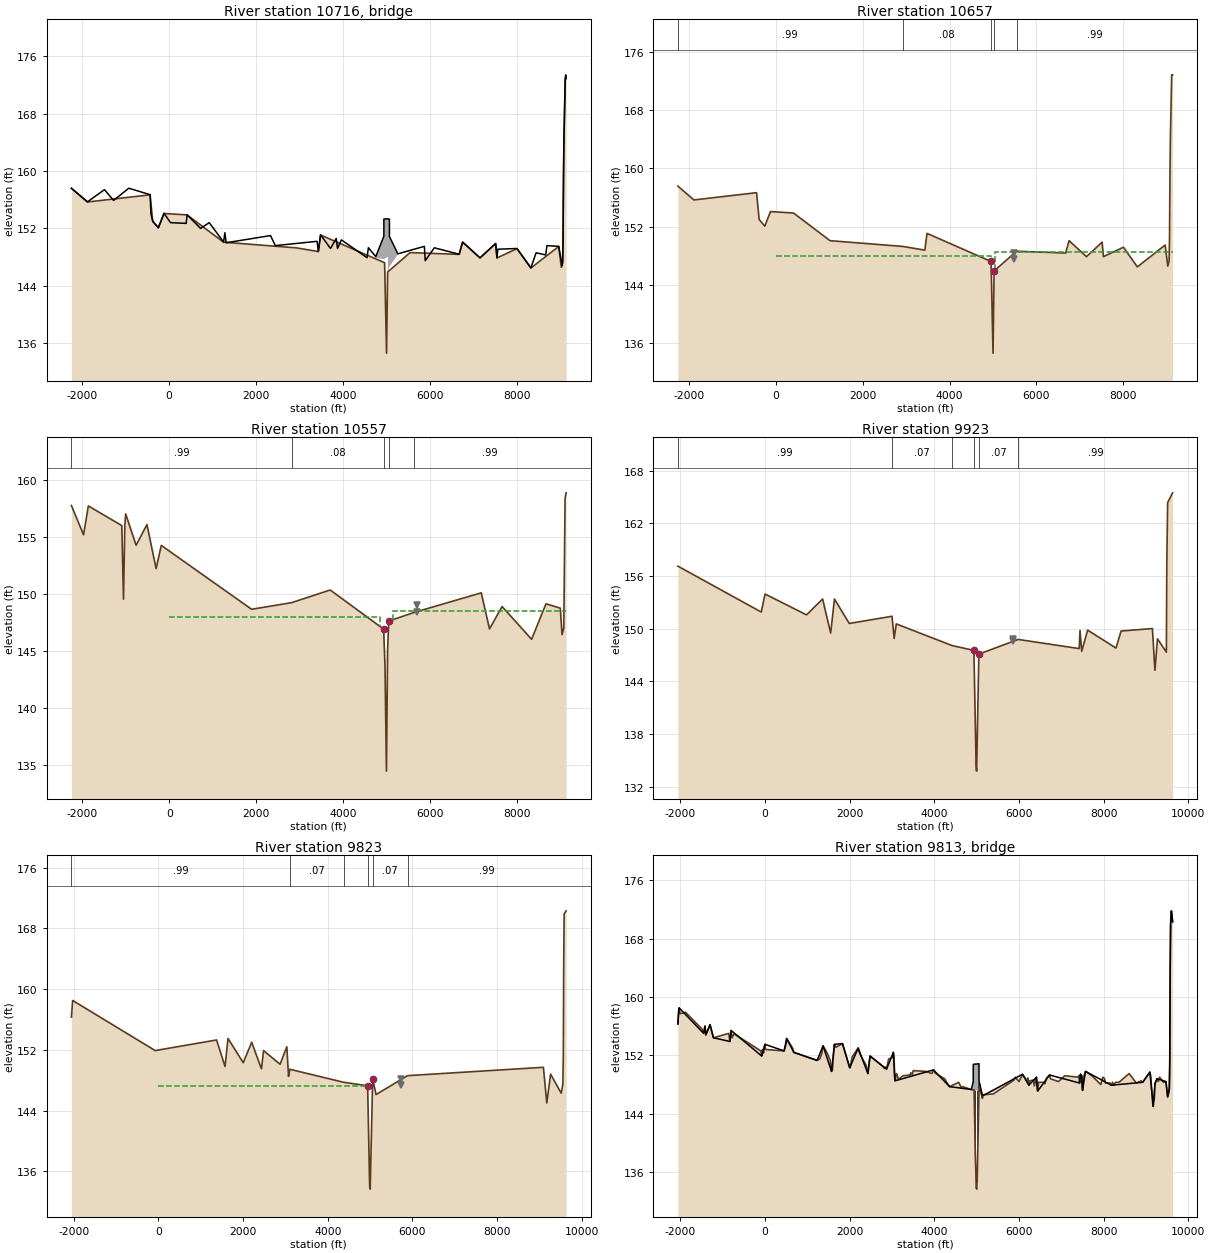
Type RM Length L Ch R = 3 ,10716   ,,,
BEGIN DESCRIPTION:
SKINNER RD
Structure ID: K145-00-00-S5-2
END DESCRIPTION:
Bridge Culvert--1,0,-1,-1, 0
Deck Dist Width WeirC Skew NumUp NumDn MinLoCord MaxHiCord MaxSubmerge Is_Ogee
10,46,2.6,0, 60, 60, , , .95, 0, ,,,
 -2247.6 -1877.6 -1487.6 -1277.6  -927.6  -437.6  -417.6  -377.6  -247.6  -117.6
    32.4   392.4   412.4   722.4   922.4  1252.4  1282.4  1312.4  2332.4  2442.4
  3402.4  3432.4  3482.4  3712.4  3842.4  3872.4  3962.4  4552.4  4582.4  4752.2
 4938.79  4938.9 5031.89    5032  5067.1 5067.21  5260.5    5870    5890    6100
    6670    6750    7150    7510    7540    7560    8000    8320    8440    8660
    8690    8960    9040    9050    9060    9070    9080    9110    9120  9130.9
   157.6   155.7   157.4   155.9   157.6   156.7     154     153   152.1   154.1
   152.8   152.7   153.9     152   152.8   150.1   151.4     150     151   149.6
   150.2   148.8   151.1   149.2   150.6   149.2   150.4  147.91  149.31  148.07
  150.91  153.31  153.34  153.34  153.26  150.86  148.46   149.5   147.5   149.3
   148.4   150.1   147.9   149.9   147.9   149.1   149.2   146.5   148.6   148.3
   149.6   149.5   146.8   147.3   150.4     159   164.3   172.9   173.4   172.9
  157.58  155.68  157.38  155.88  157.58  156.68  153.98  152.98  152.08  154.08
  152.78  152.68  153.88  151.98  152.78  150.08  151.38  149.98  150.98  149.58
  150.18  148.78  151.08  149.18  150.58  149.18  150.38  147.88  149.28   147.9
  147.71   147.7  148.07  146.04  146.66  146.67  148.35  149.48  147.48  149.28
  148.38  150.08  147.88  149.88  147.88  149.08  149.18  146.48  148.58  148.28
  149.58  149.48  146.78  147.28  150.38  158.98  164.28  172.88  173.38  172.88
 -2247.6 -1877.6 -1487.6 -1277.6  -927.6  -437.6  -417.6  -377.6  -247.6  -117.6
    32.4   392.4   412.4   722.4   922.4  1252.4  1282.4  1312.4  2332.4  2442.4
  3402.4  3432.4  3482.4  3712.4  3842.4  3872.4  3962.4  4552.4  4582.4  4752.2
 4938.79  4938.9 5031.89    5032  5067.1 5067.21  5260.5    5870    5890    6100
    6670    6750    7150    7510    7540    7560    8000    8320    8440    8660
    8690    8960    9040    9050    9060    9070    9080    9110    9120  9130.9
   157.6   155.7   157.4   155.9   157.6   156.7     154     153   152.1   154.1
   152.8   152.7   153.9     152   152.8   150.1   151.4     150     151   149.6
   150.2   148.8   151.1   149.2   150.6   149.2   150.4  147.91  149.31  148.07
  150.91  153.31  153.34  153.34  153.26  150.86  148.46   149.5   147.5   149.3
   148.4   150.1   147.9   149.9   147.9   149.1   149.2   146.5   148.6   148.3
   149.6   149.5   146.8   147.3   150.4     159   164.3   172.9   173.4   172.9
  157.58  155.68  157.38  155.88  157.58  156.68  153.98  152.98  152.08  154.08
  152.78  152.68  153.88  151.98  152.78  150.08  151.38  149.98  150.98  149.58
  150.18  148.78  151.08  149.18  150.58  149.18  150.38  147.88  149.28   147.9
  147.71   147.7  148.07  146.04  146.66  146.67  148.35  149.48  147.48  149.28
  148.38  150.08  147.88  149.88  147.88  149.08  149.18  146.48  148.58  148.28
  149.58  149.48  146.78  147.28  150.38  158.98  164.28  172.88  173.38  172.88
BR Coef= 1 , 1 , 0 ,1.25, 0 ,,,.8,0,2,0,
WSPro=,,,, 1 ,,,, 0 ,,,, 0 ,,,,-1 ,-1 ,-1 , 0 , 0 , 0 , 0 , 0
BR U #Sta/Elev= 30
 -2247.6  157.58 -1877.6  155.68  -437.6  156.68  -377.6  152.98  -247.6  152.08
  -117.6  154.08   412.4  153.88  1252.4  150.08  2922.6  149.29  3432.4  148.78
  3482.4  151.08  4955.9  147.22  5000.6  134.62  5025.4  145.92  5542.2  148.63
    6670  148.38    6750  150.08    7150  147.88    7510  149.88    7540  147.88
    8000  149.18    8320  146.48    8960  149.48    9020  146.58    9050  147.28
    9060  150.38    9070  158.98    9080  164.28    9110  172.88  9130.9  172.88
BR U #Mann= 5
 -2247.6     .99  2922.6     .08  4955.9     .02  5025.4     .06  5542.2     .99
BR U Banks=4955.9,5025.4
BR D #Sta/Elev= 30
 -2247.6  157.58 -1877.6  155.68  -437.6  156.68  -377.6  152.98  -247.6  152.08
  -117.6  154.08   412.4  153.88  1252.4  150.08  2922.6  149.29  3432.4  148.78
  3482.4  151.08  4955.9  147.22  5000.6  134.62  5025.4  145.92  5542.2  148.63
    6670  148.38    6750  150.08    7150  147.88    7510  149.88    7540  147.88
    8000  149.18    8320  146.48    8960  149.48    9020  146.58    9050  147.28
    9060  150.38    9070  158.98    9080  164.28    9110  172.88  9130.9  172.88
BR D #Mann= 5
 -2247.6     .99  2922.6     .08  4955.9     .02  5025.4     .06  5542.2     .99
BR D Banks=4955.9,5025.4
BC Design=,, 0 ,, 0 ,,,,,,
BC HTab HWMax=173.38

Type RM Length L Ch R = 1 ,10657   ,98.68,100,101.56
BEGIN DESCRIPTION:
S5-2_SKINNER RD-DS - XS2
END DESCRIPTION:
XS GIS Cut Line= 4
      3016503.77     13926420.74       3017173.7     13919240.47
      3017153.97      13919156.3      3014833.67     13915782.54
#Sta/Elev= 30
 -2247.6  157.57 -1877.6  155.67  -437.6  156.67  -377.6  152.97  -247.6  152.07
  -117.6  154.07   412.4  153.87  1252.4  150.07  2922.6  149.28  3432.4  148.77
  3482.4  151.07  4955.9  147.21  5000.6  134.61  5025.4  145.91  5542.2  148.62
    6670  148.37    6750  150.07    7150  147.87    7510  149.87    7540  147.87
    8000  149.17    8320  146.47    8960  149.47    9020  146.57    9050  147.27
    9060  150.37    9070  158.97    9080  164.27    9110  172.87  9130.9  172.87
#Mann= 5 ,-1 , 0
 -2247.6     .99       0  2922.6     .08       0  4955.9     .04       0
  5025.4     .06       0  5542.2     .99       0
Levee=0,,,-1,5487,147.55,,
#XS Ineff= 2 , 0
       0    4946     148    5042       0   148.5
Permanent Ineff=
       F       F
Bank Sta=4955.9,5025.4
XS Rating Curve= 0
Exp/Cntr=.5,.3

Type RM Length L Ch R = 1 ,10557   ,625.64,634,643.88
BEGIN DESCRIPTION:
S5-2_SKINNER RD-DS - XS1
END DESCRIPTION:
XS GIS Cut Line= 4
      3016587.04      13926374.1      3017256.97      13919193.9
      3017237.25     13919109.73      3014916.94     13915735.97
#Sta/Elev= 30
 -2254.3  157.79 -1974.3  155.22 -1864.3  157.75 -1094.3  156.03 -1054.3  149.58
 -1024.3  156.03 -1004.3  157.05  -764.3   154.3  -514.3  156.12  -304.3  152.26
  -184.3  154.29  1895.7  148.69  2815.7  149.27  3705.7  150.38  4935.7  146.95
 4966.82  143.76 5000.77   134.5    5027  145.16  5053.6  147.66  5643.6  148.42
  7183.6  150.13  7373.6  146.97  7663.6  148.93  8343.6  146.06  8673.6  149.17
  9003.6  148.79  9043.6  146.47  9083.6  147.03  9113.6  158.41  9138.2   158.9
#Mann= 5 ,-1 , 0
 -2254.3     .99       0  2815.7     .08       0  4935.7     .04       0
  5053.6     .06       0  5643.6     .99       0
Levee=0,,,-1,5693.45,149.09,,
#XS Ineff= 2 , 0
       0    4846     148    5142       0   148.5
Permanent Ineff=
       F       F
Bank Sta=4935.7,5053.6
XS Rating Curve= 0
Exp/Cntr=.3,.1

Type RM Length L Ch R = 1 ,9923    ,98.68,100,101.56
BEGIN DESCRIPTION:
S4_DRY CREEK LN-US - XS4
END DESCRIPTION:
XS GIS Cut Line= 5
      3018323.44      13926187.4      3017877.99     13919567.91
      3017888.17     13919200.15      3017888.17     13919091.06
      3015120.32     13915445.29
#Sta/Elev= 30
 -2056.2  157.13   -86.2   151.9     3.8  153.95   983.8  151.58  1363.8  153.39
  1553.8  149.51  1643.8  153.38  1993.8   150.6  3003.8  151.42  3053.8  148.89
  3103.8  150.55  4423.8  148.08  4938.3  147.53 4990.01  134.38 5001.83  133.78
  5055.3  147.11  5985.3  148.78  7425.3  147.74  7445.3   149.8  7485.3  147.43
  7625.3  149.84  8295.3   147.8  8415.3  149.74  9155.3  150.02  9215.3  145.26
  9275.3  148.85  9485.3  147.33  9495.3  157.18  9515.3  164.36  9632.7  165.48
#Mann= 6 ,-1 , 0
 -2056.2     .99       0  3003.8     .07       0  4423.8     .06       0
  4938.3     .04       0  5055.3     .07       0  5985.3     .99       0
Levee=0,,,-1,5866.02,148.81,,
#XS Ineff= 2 , 0
       0    4834   147.3    5164       0   146.4
Permanent Ineff=
       F       F
Bank Sta=4938.3,5055.3
XS Rating Curve= 0
Exp/Cntr=.5,.3

Type RM Length L Ch R = 1 ,9823    ,44,45,45
BEGIN DESCRIPTION:
S4_DRY CREEK LN-US - XS3
END DESCRIPTION:
XS GIS Cut Line= 5
      3018421.51     13926198.16      3017976.07     13919578.59
      3017986.25     13919210.83      3017986.25     13919101.74
      3015218.39     13915455.98
#Sta/Elev= 30
 -2057.2  156.31 -2027.2  158.51   -77.2  151.91  1372.8  153.31  1572.8  149.81
  1642.8  153.51  2002.8  150.31  2202.8  153.01  2432.8  149.51  2482.8  151.91
  2872.8  150.11  3032.8  152.41  3072.8  148.51  3101.6  149.45    4374  147.74
  4941.8  147.28  4989.8  133.97    5002  133.67  5060.6  148.23  5140.1  146.12
  5884.3  148.61  9094.3  149.71  9174.3  145.01  9264.3  148.81  9514.3  146.31
  9554.3  147.51  9564.3  151.01  9574.3  163.31  9584.3  169.91  9631.7  170.31
#Mann= 6 ,-1 , 0
 -2057.2     .99       0  3101.6     .07       0    4374     .06       0
  4941.8     .04       0  5060.6     .07       0  5884.3     .99       0
Levee=0,,,-1,5739,147.36,,
#XS Ineff= 2 , 0
       0    4934   147.3    5064       0   146.4
Permanent Ineff=
       F       F
Bank Sta=4941.8,5060.6
XS Rating Curve= 0
Exp/Cntr=.5,.3

Type RM Length L Ch R = 3 ,9813    ,,,
BEGIN DESCRIPTION:
DRY CREEK LN.
Structure ID: K145-00-00-S4
END DESCRIPTION:
Bridge Culvert--1,0,-1,-1, 0
Deck Dist Width WeirC Skew NumUp NumDn MinLoCord MaxHiCord MaxSubmerge Is_Ogee
10,22,2.6,0, 60, 60, , , .95, 0, ,,,
 -2057.2 -2027.2 -1447.2 -1417.2 -1397.2 -1297.2 -1217.2  -827.2  -797.2   -77.2
     2.8   452.8   512.8   682.8  1232.8  1372.8  1572.8  1642.8  1832.8  2002.8
  2202.8  2432.8  2482.8  2872.8  3032.8  3072.8  3982.8  4362.8  4876.2 4921.79
  4921.9  4924.7  5057.1  5057.7 5057.81  5140.1  6084.3  6234.3  6414.3  6444.3
  6724.3  7434.3  7454.3  7484.3  7504.3  7574.3  8184.3  8924.3  9094.3  9174.3
  9214.3  9264.3  9474.3  9514.3  9554.3  9564.3  9574.3  9584.3  9604.3  9631.7
   156.3   158.5     155     156   154.8   156.2   154.4   153.9   155.4   151.9
   153.5   152.6   154.3   152.4   151.3   153.3   149.8   153.5   153.6   150.3
     153   149.5   151.9   150.1   152.4   148.5     150   147.7  147.32  148.39
  150.69  150.77  150.84  150.81  148.51  146.44   149.4   147.9     149   147.1
   149.3   148.2   149.4   149.2   147.2   149.8   147.9   148.3   149.7     145
   148.1   148.8   148.4   146.3   147.5     151   163.3   169.9   171.8   170.3
   156.3   158.5     155     156   154.8   156.2   154.4   153.9   155.4   151.9
   153.5   152.6   154.3   152.4   151.3   153.3   149.8   153.5   153.6   150.3
     153   149.5   151.9   150.1   152.4   148.5     150   147.7  147.31  147.27
  147.27  147.27   147.2  147.38  147.41  146.11   149.4   147.9     149   147.1
   149.3   148.2   149.4   149.2   147.2   149.8   147.9   148.3   149.7     145
   148.1   148.8   148.4   146.3   147.5     151   163.3   169.9   171.8   170.3
 -2057.2 -2027.2 -1447.2 -1417.2 -1397.2 -1297.2 -1217.2  -827.2  -797.2   -77.2
     2.8   452.8   512.8   682.8  1232.8  1372.8  1572.8  1642.8  1832.8  2002.8
  2202.8  2432.8  2482.8  2872.8  3032.8  3072.8  3982.8  4362.8  4876.2 4921.79
  4921.9  4924.7  5057.1  5057.7 5057.81  5140.1  6084.3  6234.3  6414.3  6444.3
  6724.3  7434.3  7454.3  7484.3  7504.3  7574.3  8184.3  8924.3  9094.3  9174.3
  9214.3  9264.3  9474.3  9514.3  9554.3  9564.3  9574.3  9584.3  9604.3  9631.7
   156.3   158.5     155     156   154.8   156.2   154.4   153.9   155.4   151.9
   153.5   152.6   154.3   152.4   151.3   153.3   149.8   153.5   153.6   150.3
     153   149.5   151.9   150.1   152.4   148.5     150   147.7  147.32  148.39
  150.69  150.77  150.84  150.81  148.51  146.44   149.4   147.9     149   147.1
   149.3   148.2   149.4   149.2   147.2   149.8   147.9   148.3   149.7     145
   148.1   148.8   148.4   146.3   147.5     151   163.3   169.9   171.8   170.3
   156.3   158.5     155     156   154.8   156.2   154.4   153.9   155.4   151.9
   153.5   152.6   154.3   152.4   151.3   153.3   149.8   153.5   153.6   150.3
     153   149.5   151.9   150.1   152.4   148.5     150   147.7  147.31  147.27
  147.27  147.27   147.2  147.38  147.41  146.11   149.4   147.9     149   147.1
   149.3   148.2   149.4   149.2   147.2   149.8   147.9   148.3   149.7     145
   148.1   148.8   148.4   146.3   147.5     151   163.3   169.9   171.8   170.3
Pier Skew, UpSta & Num, DnSta & Num=  ,4969.5, 2 ,4969.5, 2 , 0 , 0 , 0 ,,
       2       2
  137.37   147.4
       2       2
  137.37   147.4
Pier Skew, UpSta & Num, DnSta & Num=  ,5011.6, 2 ,5011.6, 2 , 0 , 0 , 0 ,,
       2       2
  133.56  147.43
       2       2
  133.56  147.43
BR Coef= 1 , 1 , 1 ,1.25, 0 ,,,.8,0,2,0,
WSPro=,,,, 1 ,,,, 0 ,,,, 0 ,,,,-1 ,-1 ,-1 , 0 , 0 , 0 , 0 , 0
BR U #Sta/Elev= 192
 -2057.2   156.3 -2047.2   157.6 -2037.2   158.2 -2027.2   158.5 -2007.2   157.7
 -1877.2   157.9 -1487.2   155.6 -1447.2     155 -1417.2     156 -1397.2   154.8
 -1297.2   156.2 -1217.2   154.4  -857.2     155  -827.2   153.9  -807.2   155.1
  -797.2   155.4  -787.2   154.7  -777.2   154.4  -737.2   154.9  -717.2   154.9
   -97.2   152.6   -77.2   151.9   -57.2   152.8   -37.2   152.3   -27.2   152.4
   -17.2   153.2     2.8   153.5    12.8   152.8   452.8   152.6   502.8   153.6
   512.8   154.3   652.8     153   682.8   152.4  1232.8   151.3  1292.8   151.5
  1342.8   152.2  1372.8   153.3  1462.8   152.4  1542.8   151.3  1572.8   149.8
  1592.8   149.9  1632.8   153.2  1642.8   153.5  1672.8   153.1  1832.8   153.6
  2002.8   150.3  2012.8   150.3  2062.8   151.8  2202.8     153  2232.8   152.3
  2392.8   150.6  2432.8   149.5  2482.8   151.9  2782.8   150.5  2822.8   150.2
  2842.8   150.4  2872.8   150.1  2922.8   151.5  3012.8   151.7  3032.8   152.4
  3042.8   152.2  3052.8   151.3  3062.8     149  3072.8   148.5  3082.8   148.6
  3092.8   149.4  3101.6  149.44  3112.8   149.5  3152.8   148.7  3262.8   149.2
  3432.8   149.3  3442.8   149.6  3482.8   149.4  3502.8   149.9  3792.8   149.8
  3942.8   149.5  3982.8     150  4012.8   149.6  4122.8   149.2  4242.8   148.8
  4362.8   147.7    4374  147.73  4577.3   148.3  4637.3   147.6  4665.6  147.67
  4676.7   147.7  4723.5  147.61  4775.3  147.51  4827.5   147.4  4876.2  147.31
  4899.5  147.26 4921.79  147.27  4921.9  147.27 4922.01  147.27  4924.7  147.27
  4941.8  147.27 4944.61  146.39  4944.7  146.36  4969.5  138.56  4984.2  135.81
  4986.3  135.16  4988.1  134.87  4989.8  133.96  4990.1  133.95    5002  133.66
  5011.6  134.67  5011.8  134.86  5013.8  134.89  5016.4   135.4 5054.39  146.42
  5054.5  146.45  5057.1   147.2 5057.59  147.35  5057.7  147.38 5057.81  147.41
  5060.6  148.22  5081.4  147.32  5098.7  146.96  5125.6  146.41  5140.1  146.11
  5144.3   146.6  5145.6   146.6  5152.3   146.6  5394.3   146.7  5884.3   148.6
  5914.3     149  6004.3   148.4  6084.3   149.4  6194.3   148.5  6214.3   148.9
  6234.3   147.9  6254.3   148.5  6344.3   148.6  6364.3   147.8  6414.3     149
  6434.3   147.3  6444.3   147.1  6464.3   148.3  6594.3   148.3  6614.3   148.1
  6654.3   148.9  6724.3   149.3  6744.3   148.8  6934.3   148.4  7084.3   149.2
  7404.3     149  7414.3   149.2  7434.3   148.2  7454.3   149.4  7484.3   149.2
  7494.3   147.8  7504.3   147.2  7524.3     149  7574.3   149.8  7588.8  149.74
  7724.3   149.2  7934.3     148  7984.3     149  8024.3   148.8  8044.3   148.2
  8154.3   148.2  8184.3   147.9  8214.3   148.3  8234.3   147.9  8284.3   148.3
  8364.3   148.3  8604.3   149.5  8774.3   148.2  8884.3   148.5  8924.3   148.3
  9094.3   149.7  9114.3   149.2  9164.3   145.2  9174.3     145  9184.3   145.9
  9194.3   145.9  9204.3   146.5  9214.3   148.1  9264.3   148.8  9294.3   148.4
  9324.3     149  9414.3   148.3  9474.3   148.4  9514.3   146.3  9544.3   146.9
  9554.3   147.5  9564.3     151  9574.3   163.3  9584.3   169.9  9594.3   171.7
  9604.3   171.8  9631.7   170.3
BR U #Mann= 6
 -2057.2     .99  3101.6     .07    4374     .06  4941.8     .04  5060.6     .07
  5884.3     .99
BR U Banks=4941.8,5060.6
BR D #Sta/Elev= 192
 -2057.2   156.3 -2047.2   157.6 -2037.2   158.2 -2027.2   158.5 -2007.2   157.7
 -1877.2   157.9 -1487.2   155.6 -1447.2     155 -1417.2     156 -1397.2   154.8
 -1297.2   156.2 -1217.2   154.4  -857.2     155  -827.2   153.9  -807.2   155.1
  -797.2   155.4  -787.2   154.7  -777.2   154.4  -737.2   154.9  -717.2   154.9
   -97.2   152.6   -77.2   151.9   -57.2   152.8   -37.2   152.3   -27.2   152.4
   -17.2   153.2     2.8   153.5    12.8   152.8   452.8   152.6   502.8   153.6
   512.8   154.3   652.8     153   682.8   152.4  1232.8   151.3  1292.8   151.5
  1342.8   152.2  1372.8   153.3  1462.8   152.4  1542.8   151.3  1572.8   149.8
  1592.8   149.9  1632.8   153.2  1642.8   153.5  1672.8   153.1  1832.8   153.6
  2002.8   150.3  2012.8   150.3  2062.8   151.8  2202.8     153  2232.8   152.3
  2392.8   150.6  2432.8   149.5  2482.8   151.9  2782.8   150.5  2822.8   150.2
  2842.8   150.4  2872.8   150.1  2922.8   151.5  3012.8   151.7  3032.8   152.4
  3042.8   152.2  3052.8   151.3  3062.8     149  3072.8   148.5  3082.8   148.6
  3092.8   149.4  3101.6  149.44  3112.8   149.5  3152.8   148.7  3262.8   149.2
  3432.8   149.3  3442.8   149.6  3482.8   149.4  3502.8   149.9  3792.8   149.8
  3942.8   149.5  3982.8     150  4012.8   149.6  4122.8   149.2  4242.8   148.8
  4362.8   147.7    4374  147.73  4577.3   148.3  4637.3   147.6  4665.6  147.67
  4676.7   147.7  4723.5  147.61  4775.3  147.51  4827.5   147.4  4876.2  147.31
  4899.5  147.26 4921.79  147.27  4921.9  147.27 4922.01  147.27  4924.7  147.27
  4941.8  147.27 4944.61  146.39  4944.7  146.36  4969.5  138.56  4984.2  135.81
  4986.3  135.16  4988.1  134.87  4989.8  133.96  4990.1  133.95    5002  133.66
  5011.6  134.67  5011.8  134.86  5013.8  134.89  5016.4   135.4 5054.39  146.42
  5054.5  146.45  5057.1   147.2 5057.59  147.35  5057.7  147.38 5057.81  147.41
  5060.6  148.22  5081.4  147.32  5098.7  146.96  5125.6  146.41  5140.1  146.11
  5144.3   146.6  5145.6   146.6  5152.3   146.6  5394.3   146.7  5884.3   148.6
  5914.3     149  6004.3   148.4  6084.3   149.4  6194.3   148.5  6214.3   148.9
  6234.3   147.9  6254.3   148.5  6344.3   148.6  6364.3   147.8  6414.3     149
  6434.3   147.3  6444.3   147.1  6464.3   148.3  6594.3   148.3  6614.3   148.1
  6654.3   148.9  6724.3   149.3  6744.3   148.8  6934.3   148.4  7084.3   149.2
  7404.3     149  7414.3   149.2  7434.3   148.2  7454.3   149.4  7484.3   149.2
  7494.3   147.8  7504.3   147.2  7524.3     149  7574.3   149.8  7588.8  149.74
  7724.3   149.2  7934.3     148  7984.3     149  8024.3   148.8  8044.3   148.2
  8154.3   148.2  8184.3   147.9  8214.3   148.3  8234.3   147.9  8284.3   148.3
  8364.3   148.3  8604.3   149.5  8774.3   148.2  8884.3   148.5  8924.3   148.3
  9094.3   149.7  9114.3   149.2  9164.3   145.2  9174.3     145  9184.3   145.9
  9194.3   145.9  9204.3   146.5  9214.3   148.1  9264.3   148.8  9294.3   148.4
  9324.3     149  9414.3   148.3  9474.3   148.4  9514.3   146.3  9544.3   146.9
  9554.3   147.5  9564.3     151  9574.3   163.3  9584.3   169.9  9594.3   171.7
  9604.3   171.8  9631.7   170.3
BR D #Mann= 6
 -2057.2     .99  3101.6     .07    4374     .06  4941.8     .04  5060.6     .07
  5884.3     .99
BR D Banks=4941.8,5060.6
BC Design=,, 0 ,, 0 ,,,,,,
BC HTab HWMax=171.81

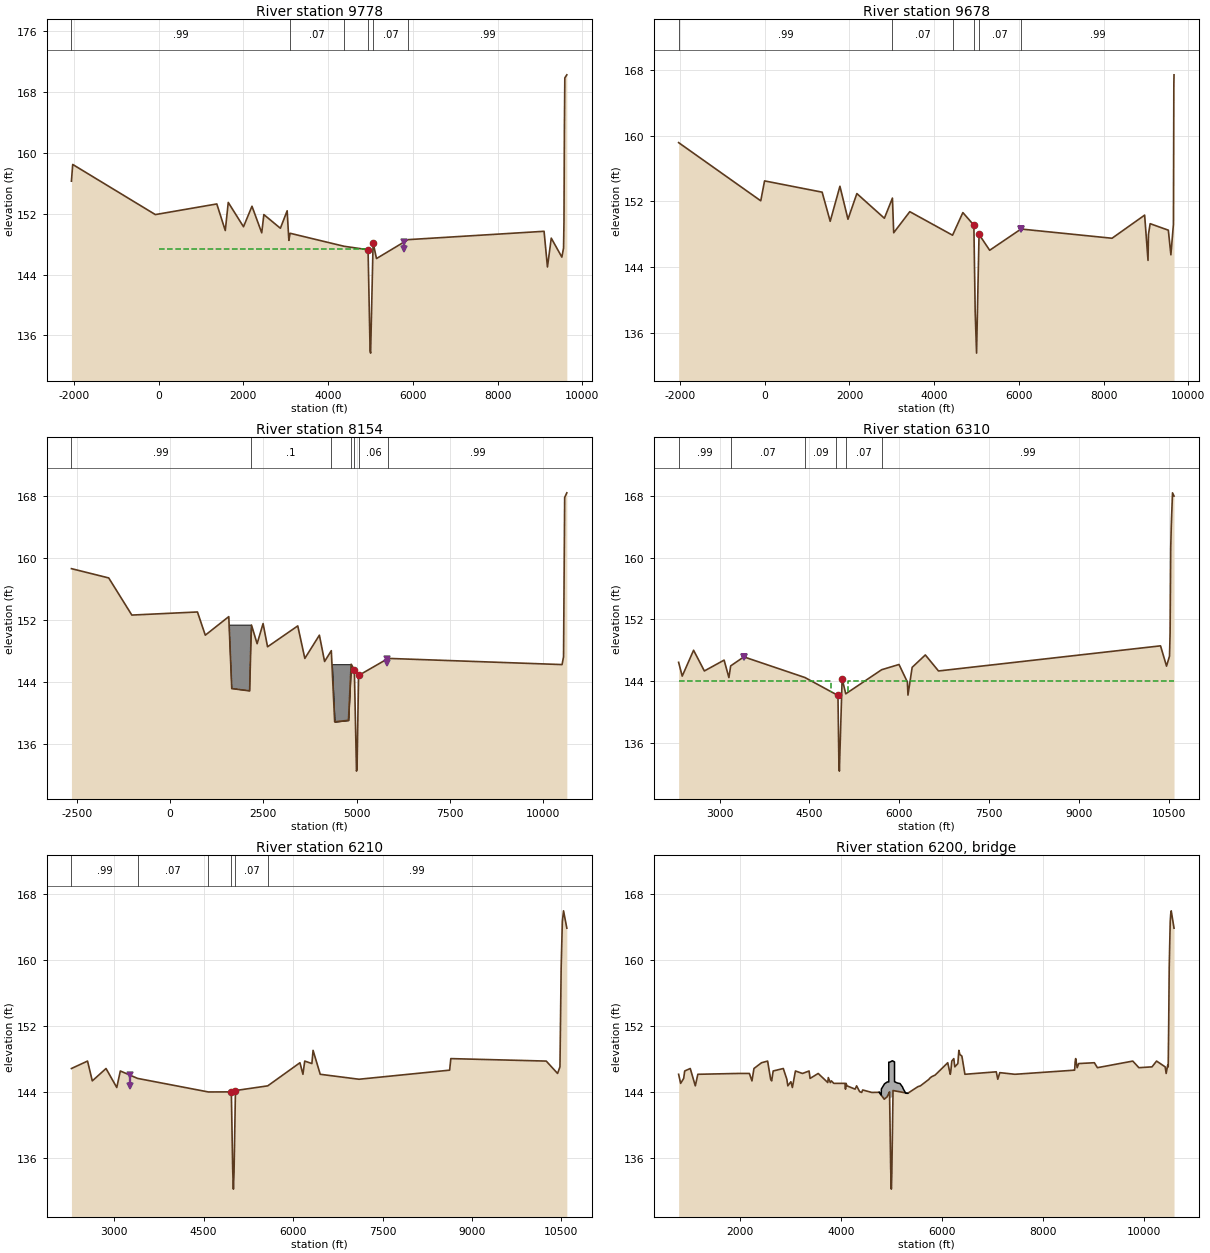
Type RM Length L Ch R = 1 ,9778    ,99.19,100,100
BEGIN DESCRIPTION:
S4_DRY CREEK LN-DS - XS2
END DESCRIPTION:
XS GIS Cut Line= 5
      3018465.52     13926196.82      3018020.13     13919578.19
      3018030.29      13919211.1      3018030.29     13919095.01
      3015258.37     13915443.88
#Sta/Elev= 30
 -2057.2  156.29 -2027.2  158.49   -77.2  151.89  1372.8  153.29  1572.8  149.79
  1642.8  153.49  2002.8  150.29  2202.8  152.99  2432.8  149.49  2482.8  151.89
  2872.8  150.09  3032.8  152.39  3072.8  148.49  3101.6  149.43    4374  147.72
  4941.8  147.26  4989.8  133.95    5002  133.65  5060.6  148.21  5140.1   146.1
  5884.3  148.59  9094.3  149.69  9174.3  144.99  9264.3  148.79  9514.3  146.29
  9554.3  147.49  9564.3  150.99  9574.3  163.29  9584.3  169.89  9631.7  170.29
#Mann= 6 ,-1 , 0
 -2057.2     .99       0  3101.6     .07       0    4374     .06       0
  4941.8     .04       0  5060.6     .07       0  5884.3     .99       0
Levee=0,,,-1,5788,147.36,,
#XS Ineff= 2 , 0
       0    4934   147.3    5064       0   146.4
Permanent Ineff=
       F       F
Bank Sta=4941.8,5060.6
XS Rating Curve= 0
Exp/Cntr=.5,.3

Type RM Length L Ch R = 1 ,9678    ,1511.74,1524.01,1524.01
BEGIN DESCRIPTION:
S4_DRY CREEK LN-DS - XS1
END DESCRIPTION:
XS GIS Cut Line= 5
      3018564.56      13926158.9      3018119.18     13919540.32
      3018129.34     13919173.23      3018129.34     13919057.14
      3015357.41     13915406.01
#Sta/Elev= 30
 -2035.5  159.15   -95.5  152.08    -5.5   154.5  1354.5  153.13  1544.5  149.59
  1774.5  153.85  1964.5  149.84  2174.5  152.96  2824.5  149.96  3014.5  152.41
  3044.5   148.2  3424.5  150.76  4434.5   147.9  4678.1  150.65  4938.1  149.12
 4969.39  138.52  5001.8  133.57 5060.22     148  5311.4  146.07  6051.4  148.65
  8201.4  147.53  8971.4  150.34  9051.4  144.84  9061.4  147.98  9101.4   149.3
  9531.4  148.51  9591.4  145.52  9651.4  149.23  9661.4   166.3  9665.6  167.39
#Mann= 6 ,-1 , 0
 -2035.5     .99       0  3014.5     .07       0  4434.5     .06       0
  4938.1     .04       0 5060.22     .07       0  6051.4     .99       0
Levee=0,,,-1,6051.06,148.66,,
#XS Ineff= 2 , 0
       0    4834   147.3    5164       0   146.4
Permanent Ineff=
       F       F
Bank Sta=4938.1,5060.22
XS Rating Curve= 0
Exp/Cntr=.3,.1

Type RM Length L Ch R = 1 ,8154    ,1844,1844,1798.47
BEGIN DESCRIPTION:
Cross Section K145-00-00-X3
END DESCRIPTION:
XS GIS Cut Line= 5
      3018751.04       13926264.      3019549.07     13918739.48
      3019553.93     13918630.31      3019323.96      13917644.2
      3015352.61      13915326.5
#Sta/Elev= 30
 -2646.6   158.6 -1646.6   157.4 -1026.6   152.6   733.4     153   943.4     150
  1573.4   152.4  1653.4   143.1  2133.4   142.8  2163.4   148.4  2183.4   151.3
  2333.4   148.9  2493.4   151.5  2613.4   148.5  3423.4   151.2  3613.4     147
  4003.4     150  4143.4   146.6  4323.4     148  4413.4   138.8  4783.4     139
  4855.9  146.25  4941.2  145.54  4998.7  132.43  5013.2   132.7  5054.4  144.79
  5849.4     147   10512   146.2   10552   147.2   10582   167.8 10640.2   168.4
#Mann= 7 ,-1 , 0
 -2646.6     .99       0  2163.4      .1       0  4323.4    .026       0
  4855.9     .06       0  4941.2     .04       0  5054.4     .06       0
  5849.4     .99       0
Levee=0,,,-1,5812,146.45,,
#Block Obstruct= 2 ,-1
  1588.4  2185.2   151.3    4329  4855.9  146.25
Bank Sta=4941.2,5054.4
XS Rating Curve= 0
Exp/Cntr=.3,.1

Type RM Length L Ch R = 1 ,6310    ,100,100,97.53
BEGIN DESCRIPTION:
S2_SPRING CYPRESS-US - XS4
END DESCRIPTION:
XS GIS Cut Line= 4
      3022356.77      13919519.7       3020553.7     13917592.92
      3020479.35     13917563.72      3015422.64     13915287.71
#Sta/Elev= 30
  2313.7  146.42  2373.7  144.63  2563.7  147.99  2743.7   145.3  3073.7  146.71
  3153.7  144.44  3183.7  145.96  3403.7  147.13  4423.7  144.45  4943.7  142.26
  4975.9  142.17  4990.4  134.01 4999.36   132.3  5045.7  144.31  5105.7  142.33
  5705.7  145.46  5995.7  146.14  6135.7  143.87  6145.7  142.17  6215.7  145.77
  6435.7  147.38  6655.7   145.3 10365.7  148.56 10465.7  145.93 10515.7  147.24
 10525.7  150.24 10535.7  161.22 10545.7  164.29 10565.7  168.42   10591     168
#Mann= 6 ,-1 , 0
  2313.7     .99       0  3183.7     .07       0  4423.7     .09       0
  4943.7     .04       0  5105.7     .07       0  5705.7     .99       0
Levee=-1,3406.73,147.16,0,,,,
#XS Ineff= 2 , 0
       0    4856     144    5142       0     144
Permanent Ineff=
       F       F
Bank Sta=4975.9,5045.7
XS Rating Curve= 0
Exp/Cntr=.5,.3

Type RM Length L Ch R = 1 ,6210    ,61,61,61
BEGIN DESCRIPTION:
S2_SPRING CYPRESS-US - XS3
END DESCRIPTION:
XS GIS Cut Line= 4
      3022425.59      13919448.9      3020594.77     13917492.41
      3020520.42      13917463.2      3015463.71      13915187.2
#Sta/Elev= 30
  2283.5   146.9  2553.5   147.8  2633.5   145.4  2863.5   146.9  3043.5   144.6
  3103.5   146.6  3393.5   145.7    4580  144.06  4964.8  144.07  4987.4  134.78
  4999.4  132.29    5010  134.21  5033.9  144.23  5575.5   144.8  6115.5   147.6
  6165.5   146.2  6195.5   147.8  6315.5   147.5  6335.5   149.1  6455.5   146.2
  7105.5   145.6  8625.5   146.7  8645.5   148.1 10245.5   147.8 10435.5   146.3
 10475.5   147.1 10495.5   159.1 10515.5   164.7 10535.5     166 10590.8   163.9
#Mann= 6 ,-1 , 0
  2283.5     .99       0  3393.5     .07       0    4580     .09       0
  4964.8     .04       0  5033.9     .07       0  5575.5     .99       0
Levee=-1,3266,144.81,0,,,,
#XS Ineff= 2 , 0
       0    4956     144    5042       0   143.9
Permanent Ineff=
       F       F
Bank Sta=4964.8,5033.9
XS Rating Curve= 0
Exp/Cntr=.5,.3

Type RM Length L Ch R = 3 ,6200    ,,,
BEGIN DESCRIPTION:
SPRING CYPRESS **SEE NOTE**
The n-value on the downstream internal XS was increased to 0.05 to account for the pipeline.
Structure ID: K145-00-00-S2
END DESCRIPTION:
Bridge Culvert--1,0,-1,-1, 0
Deck Dist Width WeirC Skew NumUp NumDn MinLoCord MaxHiCord MaxSubmerge Is_Ogee
10,40,2.6,0, 42, 42, , , .95, 0, ,,,
  4759.7  4780.4  4800.4  4803.2  4859.8  4865.4  4914.7  4923.4 4949.09  4949.2
 4949.31  4964.8 4966.81  4966.9  4967.3  4987.4  4995.3  4995.6  4996.3  4999.4
  5002.8  5004.3  5004.6    5010  5020.3 5031.69  5031.8  5033.9 5063.29  5063.4
 5063.51  5070.6  5072.4  5118.6  5121.7  5171.7  5223.3  5230.4  5285.5  5295.5
  5305.5  5325.5
  144.03  143.86  143.69  144.42  144.99  145.05  145.25  145.28  145.27  147.67
  147.67  147.67  147.67  147.67  147.67  147.73  147.76  147.76  147.76  147.77
  147.78  147.79  147.79  147.81  147.84   147.8   147.8   147.8   147.7   147.7
   145.3  145.28  145.27  145.15  145.14  145.08  144.64   144.5   143.9   143.9
   143.9   143.9
  144.02  143.85  143.68  143.65  143.18  143.21  143.45  143.56  143.88  143.88
  143.88  144.07  143.24  143.27  143.27  143.33  143.36  143.36  143.36  143.37
  143.38  143.39  143.39  143.41  143.44   143.4  143.35  144.23  143.78  143.78
  143.78  143.67  143.62  142.37   142.4  142.97  143.55  143.63   143.8   142.5
   142.7   143.9
  4759.7  4780.4  4800.4  4803.2  4859.8  4865.4  4914.7  4923.4 4949.09  4949.2
 4949.31  4964.8 4966.81  4966.9  4967.3  4987.4  4995.3  4995.6  4996.3  4999.4
  5002.8  5004.3  5004.6    5010  5020.3 5031.69  5031.8  5033.9 5063.29  5063.4
 5063.51  5070.6  5072.4  5118.6  5121.7  5171.7  5223.3  5230.4  5285.5  5295.5
  5305.5  5325.5
  144.03  143.86  143.69  144.42  144.99  145.05  145.25  145.28  145.27  147.67
  147.67  147.67  147.67  147.67  147.67  147.73  147.76  147.76  147.76  147.77
  147.78  147.79  147.79  147.81  147.84   147.8   147.8   147.8   147.7   147.7
   145.3  145.28  145.27  145.15  145.14  145.08  144.64   144.5   143.9   143.9
   143.9   143.9
                                                                                
                          143.27  143.27  143.33  143.36  143.36  143.36  143.37
  143.38  143.39  143.39  143.41  143.44   143.4
                                                                                
                
BR Coef= 1 , 1 , 0 ,1.25, 0 ,,,.8,0,2,0,
WSPro=,,,, 1 ,,,, 0 ,,,, 0 ,,,,-1 ,-1 ,-1 , 0 , 0 , 0 , 0 , 0
BR U #Sta/Elev= 116
   793.5   146.2   833.5   145.1   893.5   145.7   913.5   146.6  1023.5   146.9
  1123.5   144.8  1173.5   146.2  1963.5   146.3  2193.5   146.3  2243.5   145.4
  2283.5   146.9  2433.5   147.6  2553.5   147.8  2613.5   145.6  2633.5   145.4
  2663.5   146.6  2863.5   146.9  2933.5   145.6  2953.5   144.8  3013.5   145.3
  3043.5   144.6  3103.5   146.6  3243.5   146.3  3373.5   146.6  3386.8     146
  3393.5   145.7  3553.5   146.3  3743.5   145.2  3753.5   145.8  3793.5   145.2
  3813.5   145.4  3863.5   145.1  4083.5   145.1  4093.5   144.4  4103.5   145.1
  4123.5   144.8  4283.5   144.4  4313.5   144.8  4373.5   144.1  4413.5     144
  4433.5   144.3    4580  144.06  4613.5     144  4759.7  144.02  4780.4  143.85
  4800.4  143.68  4803.2  143.65  4859.8  143.18  4865.4  143.21  4914.7  143.45
  4923.4  143.56 4949.09  143.88  4949.2  143.88 4949.31  143.88  4964.8  144.07
 4966.81  143.24  4966.9  143.21  4967.3  143.04  4987.4  134.78  4995.3  133.03
  4995.6  132.94  4996.3  132.67  4999.4  132.29  5002.8  132.47  5004.3  132.96
  5004.6  133.01    5010  134.21  5020.3  138.53 5031.69   143.3  5031.8  143.35
  5033.9  144.23  5325.5   143.9  5525.5   144.7  5575.5   144.8  5745.5   145.6
  5755.5   145.7  5795.5   145.9    5826  145.99  5865.5   146.1  6115.5   147.6
  6165.5   146.2  6175.5   146.5  6195.5   147.8  6235.5   148.1  6255.5   147.1
  6315.5   147.5  6335.5   149.1  6355.5   148.6  6395.5   148.4  6455.5   146.2
  7075.5   146.5  7105.5   145.6  7145.5   146.4  7445.5   146.2  8621.4   146.7
  8625.5   146.7  8635.5   147.7  8645.5   148.1  8675.5     147  8705.5   147.5
  9015.5   147.6  9075.5     147  9775.5   147.8  9895.5     147 10155.5   147.1
 10245.5   147.8 10415.5   147.1 10435.5   146.3 10465.5   147.3 10475.5   147.1
 10485.5   152.2 10495.5   159.1 10515.5   164.7 10525.5   165.6 10535.5     166
 10590.8   163.9
BR U #Mann= 6
   793.5     .99  3393.5     .07    4580     .09  4964.8     .04  5033.9     .07
  5525.5     .99
BR U Banks=4964.8,5033.9
BR D #Sta/Elev= 116
   793.5   146.2   833.5   145.1   893.5   145.7   913.5   146.6  1023.5   146.9
  1123.5   144.8  1173.5   146.2  1963.5   146.3  2193.5   146.3  2243.5   145.4
  2283.5   146.9  2433.5   147.6  2553.5   147.8  2613.5   145.6  2633.5   145.4
  2663.5   146.6  2863.5   146.9  2933.5   145.6  2953.5   144.8  3013.5   145.3
  3043.5   144.6  3103.5   146.6  3243.5   146.3  3373.5   146.6  3386.8     146
  3393.5   145.7  3553.5   146.3  3743.5   145.2  3753.5   145.8  3793.5   145.2
  3813.5   145.4  3863.5   145.1  4083.5   145.1  4093.5   144.4  4103.5   145.1
  4123.5   144.8  4283.5   144.4  4313.5   144.8  4373.5   144.1  4413.5     144
  4433.5   144.3    4580  144.06  4613.5     144  4759.7  144.02  4780.4  143.85
  4800.4  143.68  4803.2  143.65  4859.8  143.18  4865.4  143.21  4914.7  143.45
  4923.4  143.56 4949.09  143.88  4949.2  143.88 4949.31  143.88  4964.8  144.07
 4966.81  142.82 4966.89  142.79  4967.3  142.62  4987.4  134.36  4995.3  132.61
  4995.6  132.52  4996.3  132.25  4999.4  131.87  5002.8  132.05  5004.3  132.54
  5004.6  132.59    5010  133.79  5020.3  138.11 5031.68  142.88  5031.8  142.93
  5033.9  144.23  5325.5   143.9  5525.5   144.7  5575.5   144.8  5745.5   145.6
  5755.5   145.7  5795.5   145.9    5826  145.99  5865.5   146.1  6115.5   147.6
  6165.5   146.2  6175.5   146.5  6195.5   147.8  6235.5   148.1  6255.5   147.1
  6315.5   147.5  6335.5   149.1  6355.5   148.6  6395.5   148.4  6455.5   146.2
  7075.5   146.5  7105.5   145.6  7145.5   146.4  7445.5   146.2  8621.4   146.7
  8625.5   146.7  8635.5   147.7  8645.5   148.1  8675.5     147  8705.5   147.5
  9015.5   147.6  9075.5     147  9775.5   147.8  9895.5     147 10155.5   147.1
 10245.5   147.8 10415.5   147.1 10435.5   146.3 10465.5   147.3 10475.5   147.1
 10485.5   152.2 10495.5   159.1 10515.5   164.7 10525.5   165.6 10535.5     166
 10590.8   163.9
BR D #Mann= 5
   793.5     .99  3386.8     .06  4964.8     .05  5033.9     .06  5525.5     .99
BR D Banks=4964.8,5033.9
BC Design=,, 0 ,, 0 ,,,,,,
BC HTab HWMax=166