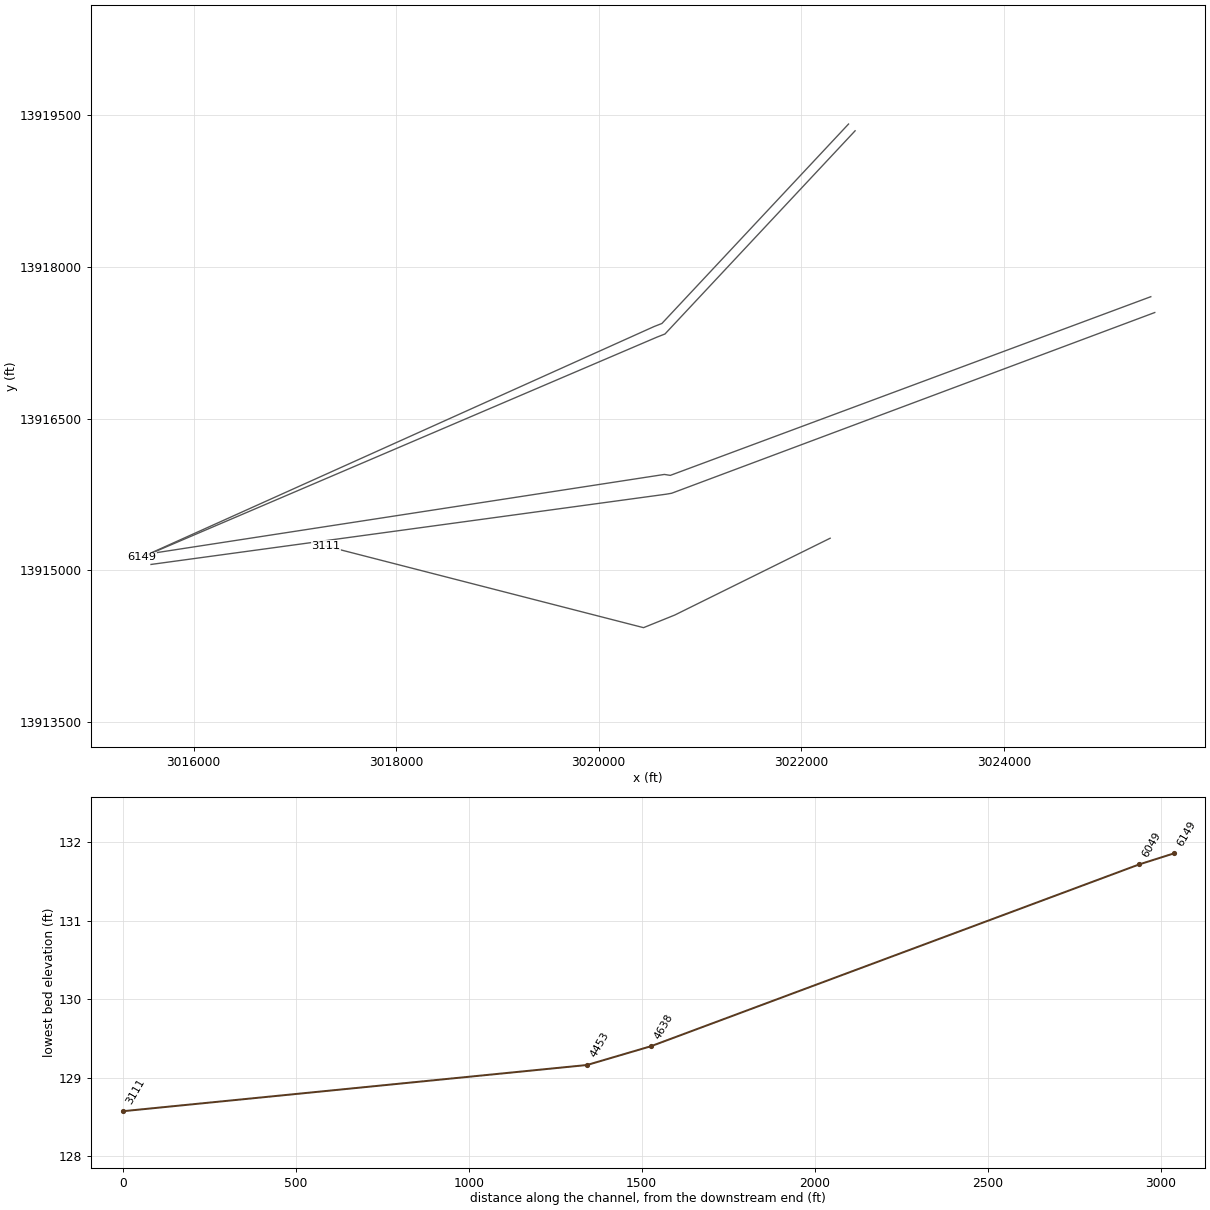
HEC-RAS study k145-00-00.prj: K145-00-00

--- k145-00-00.g01 (geometry) --- (continued)

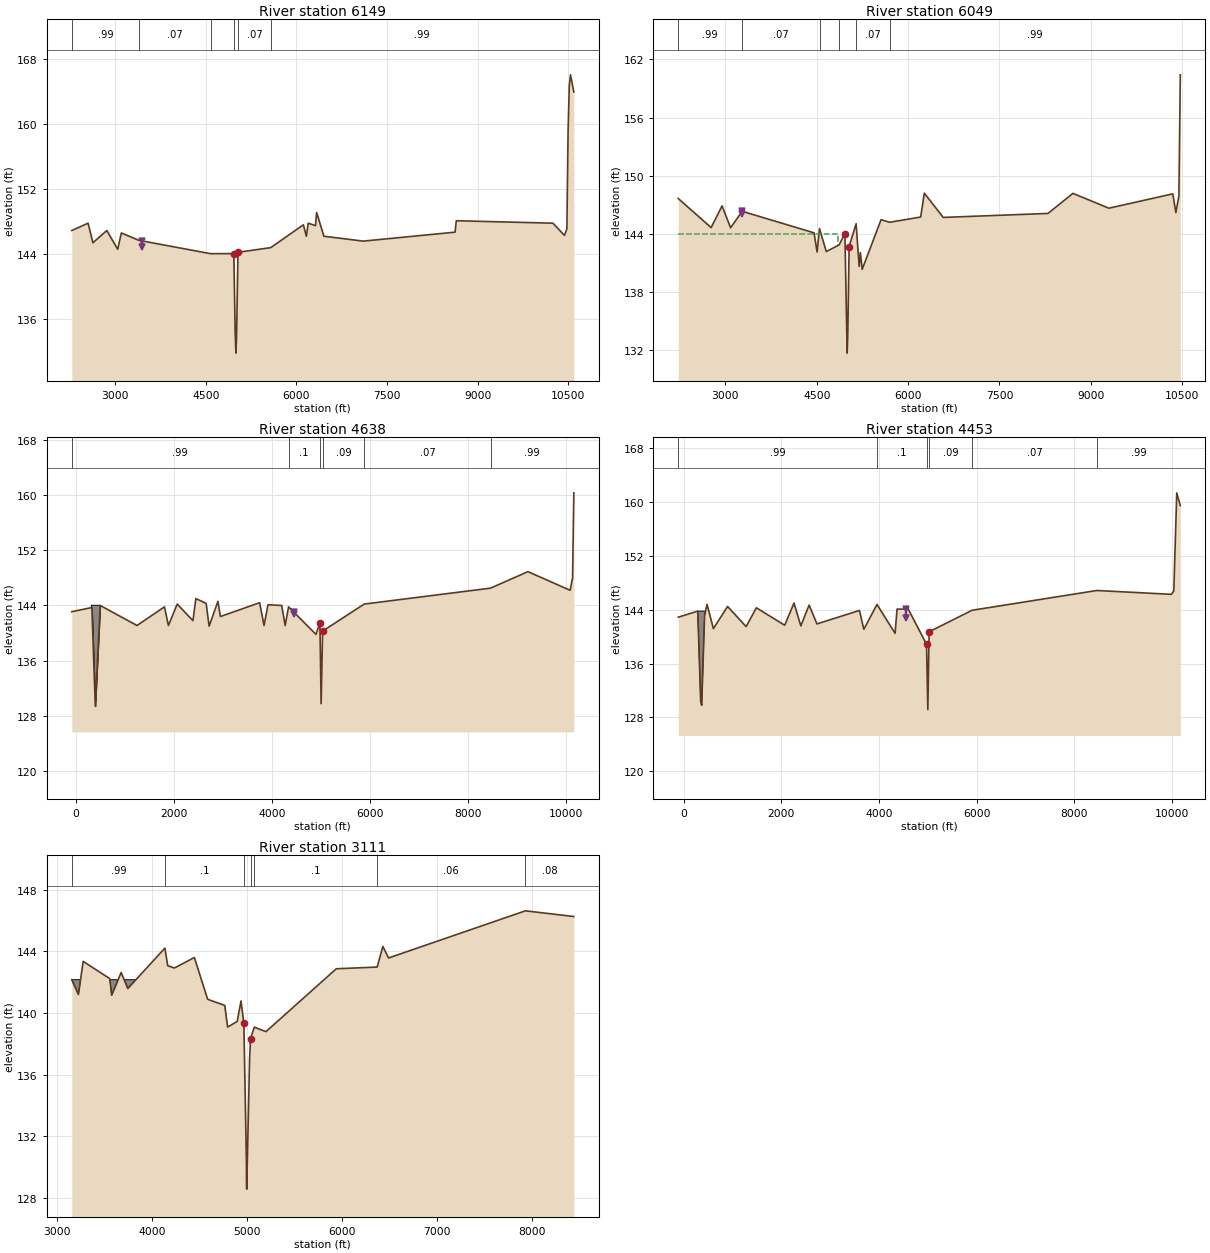
Type RM Length L Ch R = 1 ,6149    ,102.38,100,94.04
BEGIN DESCRIPTION:
S2_SPRING CYPRESS-DS - XS2
END DESCRIPTION:
XS GIS Cut Line= 4
      3022466.15      13919407.1      3020623.91     13917438.47
      3020545.82     13917407.79      3015489.55     13915131.98
#Sta/Elev= 30
  2283.5   146.9  2553.5   147.8  2633.5   145.4  2863.5   146.9  3043.5   144.6
  3103.5   146.6  3393.5   145.7    4580  144.06  4964.8  144.07  4987.4  134.35
  4999.4  131.86    5010  133.78  5033.9  144.23  5575.5   144.8  6115.5   147.6
  6165.5   146.2  6195.5   147.8  6315.5   147.5  6335.5   149.1  6455.5   146.2
  7105.5   145.6  8625.5   146.7  8645.5   148.1 10245.5   147.8 10435.5   146.3
 10475.5   147.1 10495.5   159.1 10515.5   164.7 10535.5     166 10590.8   163.9
#Mann= 6 ,-1 , 0
  2283.5     .99       0  3393.5     .07       0    4580     .09       0
  4964.8     .04       0  5033.9     .07       0  5575.5     .99       0
Levee=-1,3450.86,144.82,0,,,,
#XS Ineff= 2 , 0
       0    4956     144    5042       0   143.9
Permanent Ineff=
       F       F
Bank Sta=4964.8,5033.9
XS Rating Curve= 0
Exp/Cntr=.5,.3

Type RM Length L Ch R = 1 ,6049    ,1444.62,1411,1326.96
BEGIN DESCRIPTION:
S2_SPRING CYPRESS-DS - XS1
END DESCRIPTION:
XS GIS Cut Line= 4
      3022531.02      13919340.4      3020654.18     13917334.71
      3020576.08     13917304.03      3015589.34     13915172.77
#Sta/Elev= 30
  2225.9  147.66  2765.9  144.66  2945.9   146.9  3085.9  144.64  3275.9  146.34
  4455.9  144.12  4505.9  142.15  4545.9  144.56  4655.9  142.19  4865.9  142.87
  4962.6  144.05 4999.45  131.72 5009.96   133.7 5031.58   142.7  5146.5  145.06
  5196.5  140.67  5216.5  142.08  5246.5  140.36  5556.5  145.48  5696.5  145.21
  6206.5  145.75  6266.5  148.21  6576.5  145.71  8296.5  146.12  8706.5  148.19
  9296.5  146.66 10346.5  148.14 10396.5  146.21 10446.5  147.91 10469.6  160.41
#Mann= 6 ,-1 , 0
  2225.9     .99       0  3275.9     .07       0  4545.9     .09       0
  4865.9     .04       0  5146.5     .07       0  5696.5     .99       0
Levee=-1,3275.71,146.04,0,,,,
#XS Ineff= 2 , 0
       0    4856     144    5142       0     144
Permanent Ineff=
       F       F
Bank Sta=4962.6,5031.58
XS Rating Curve= 0
Exp/Cntr=.3,.1

Type RM Length L Ch R = 1 ,4638    ,185,185,198
BEGIN DESCRIPTION:
Cross Section K145-00-00-X2
END DESCRIPTION:
XS GIS Cut Line= 4
      3025450.26      13917702.8      3020706.73     13915938.86
      3020648.26     13915948.19    3015592.1913   13915169.5511
#Sta/Elev= 30
   -83.4   143.1   326.6   143.7   396.6   129.4   496.6     144  1246.6   141.1
  1806.6   143.8  1886.6   141.1  2066.6   144.2  2386.6   141.8  2446.6     145
  2656.6   144.3  2716.6     141  2896.6   144.6  2946.6   142.4  3746.6   144.4
  3836.6   141.1  3916.6   144.1  4196.6     144  4266.6   141.1  4336.6   143.8
  4895.6  139.81  4975.4  141.51  5000.2  129.78  5030.3  140.28  5877.8   144.2
    8454  146.51  9216.7   148.9 10076.7   146.2 10126.7     14810152.37  160.32
#Mann= 6 ,-1 , 0
   -83.4     .99       0  4336.6      .1       0  4975.4     .04       0
  5030.3     .09       0  5877.8     .07       0    8454     .99       0
Levee=-1,4439.27,142.81,0,,,,
#Block Obstruct= 2 ,-1
   306.5   499.1   144.1     500     501     120
Bank Sta=4975.4,5030.3
XS Rating Curve= 0
Exp/Cntr=.3,.1

Type RM Length L Ch R = 1 ,4453    ,1310,1342,1313
BEGIN DESCRIPTION:
Cross Section K145-00-00-X1
END DESCRIPTION:
XS GIS Cut Line= 4
      3025489.32     13917546.55      3020720.21     13915762.45
       3020666.3     13915753.14      3015580.47     13915059.57
#Sta/Elev= 30
  -110.9   142.9   289.1   143.8   349.1   130.4   369.1   129.8   429.1   143.2
   479.1   144.8   609.1   141.2   899.1   144.5  1279.1   141.5  1489.1   144.3
  2069.1   141.7  2259.1     145  2399.1   141.6  2569.1   144.7  2729.1   141.9
  3599.1   143.9  3689.1   141.1  3958.5  144.79  4329.1   140.5  4369.1   144.1
  4599.1   144.1  4972.7  138.87  4999.3  129.16  5025.8  140.73  5905.2  143.93
  8459.8  146.87  9985.7   146.3 10035.7   146.8 10095.7   161.4 10168.6   159.5
#Mann= 6 ,-1 , 0
  -110.9     .99       0  3958.5      .1       0  4972.7     .04       0
  5025.8     .09       0  5905.2     .07       0  8459.8     .99       0
Levee=-1,4561.21,142.81,0,,,,
#Block Obstruct= 2 ,-1
   286.9   463.9   143.8     465     466     120
Bank Sta=4972.7,5025.8
XS Rating Curve= 0
Exp/Cntr=.3,.1

Type RM Length L Ch R = 1 ,3111    ,907.04,1043,808.48
BEGIN DESCRIPTION:
K145-Interpolated1a
END DESCRIPTION:
XS GIS Cut Line= 4
      3022284.78      13915318.4      3020750.91     13914560.21
      3020442.34     13914435.57      3017304.44     13915241.63
#Sta/Elev= 30
  3158.3  142.16  3228.3   141.2  3278.3  143.35  3558.3  142.23  3578.3  141.15
  3678.3  142.63  3748.3  141.59  4138.3  144.21  4168.3  143.07  4238.3  142.92
  4448.3   143.6  4588.3  140.89  4768.3  140.49  4798.3  139.09  4899.3  139.45
  4939.3  140.78  4969.3  139.33  4995.9  130.49  4996.9  129.08  4999.3  128.57
  5029.3  136.97  5039.3  138.33  5079.3  139.08  5202.1  138.79  5942.1  142.87
  6372.1  142.98  6432.1  144.32  6492.1  143.57  7932.1  146.63  8441.9  146.26
#Mann= 7 ,-1 , 0
  3158.3     .99       0  4138.3      .1       0  4969.3     .04       0
  5039.3     .06       0  5079.3      .1       0  6372.1     .06       0
  7932.1     .08       0
#Block Obstruct= 2 , 0
       0    4150  142.16               0
Bank Sta=4969.3,5039.3
XS Rating Curve= 0
Exp/Cntr=.3,.1