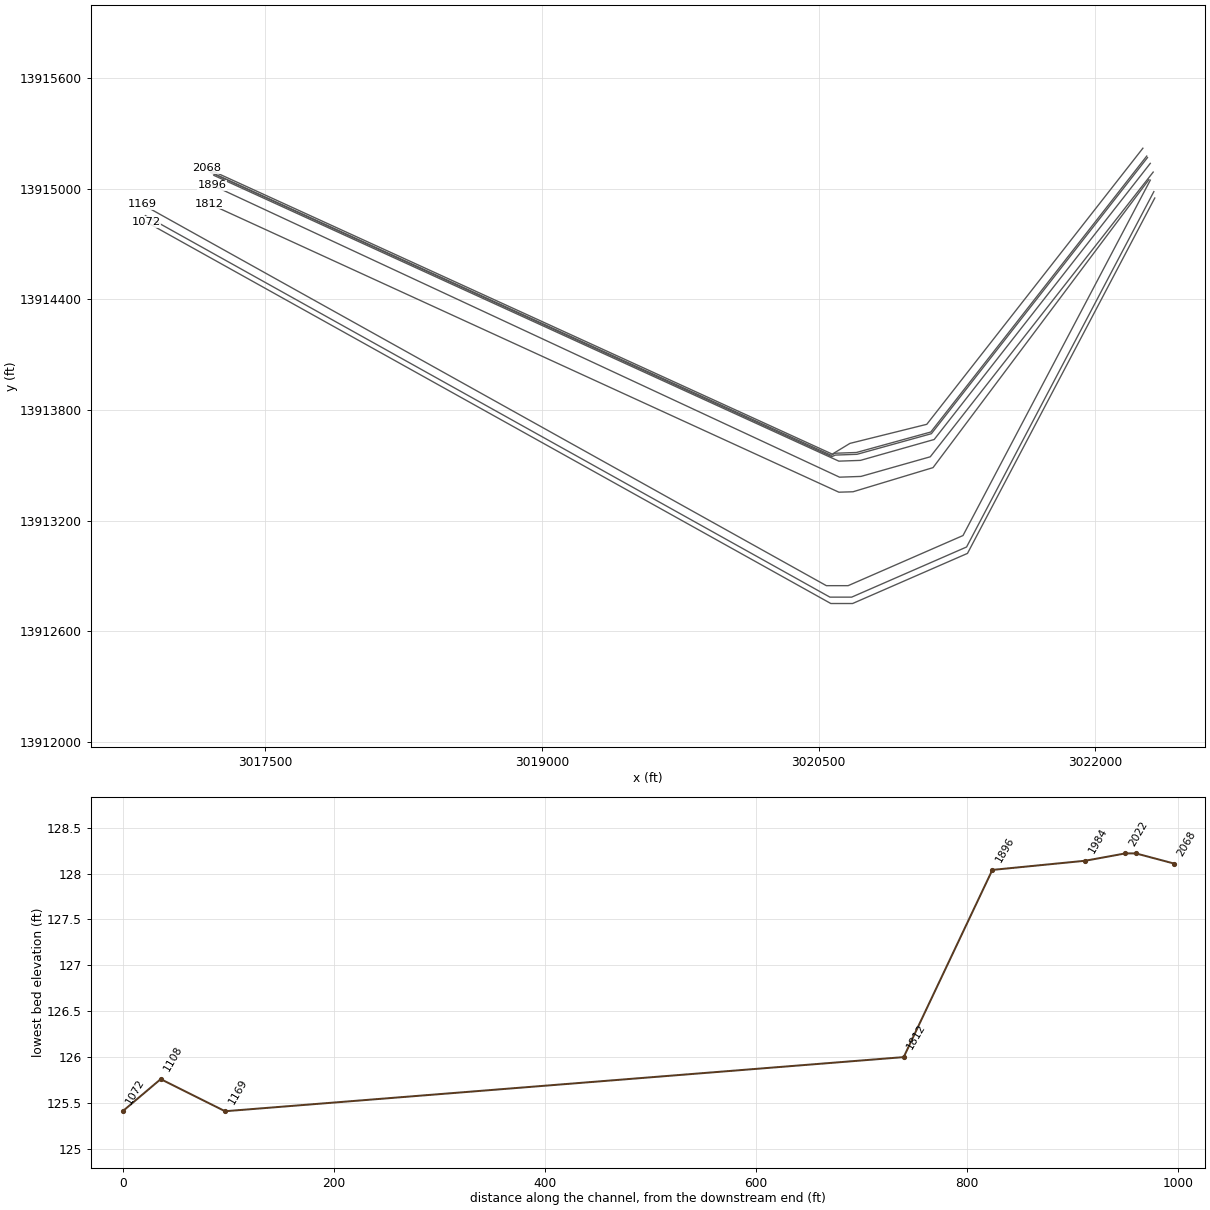
HEC-RAS study k145-00-00.prj: K145-00-00

--- k145-00-00.g01 (geometry) --- (continued)

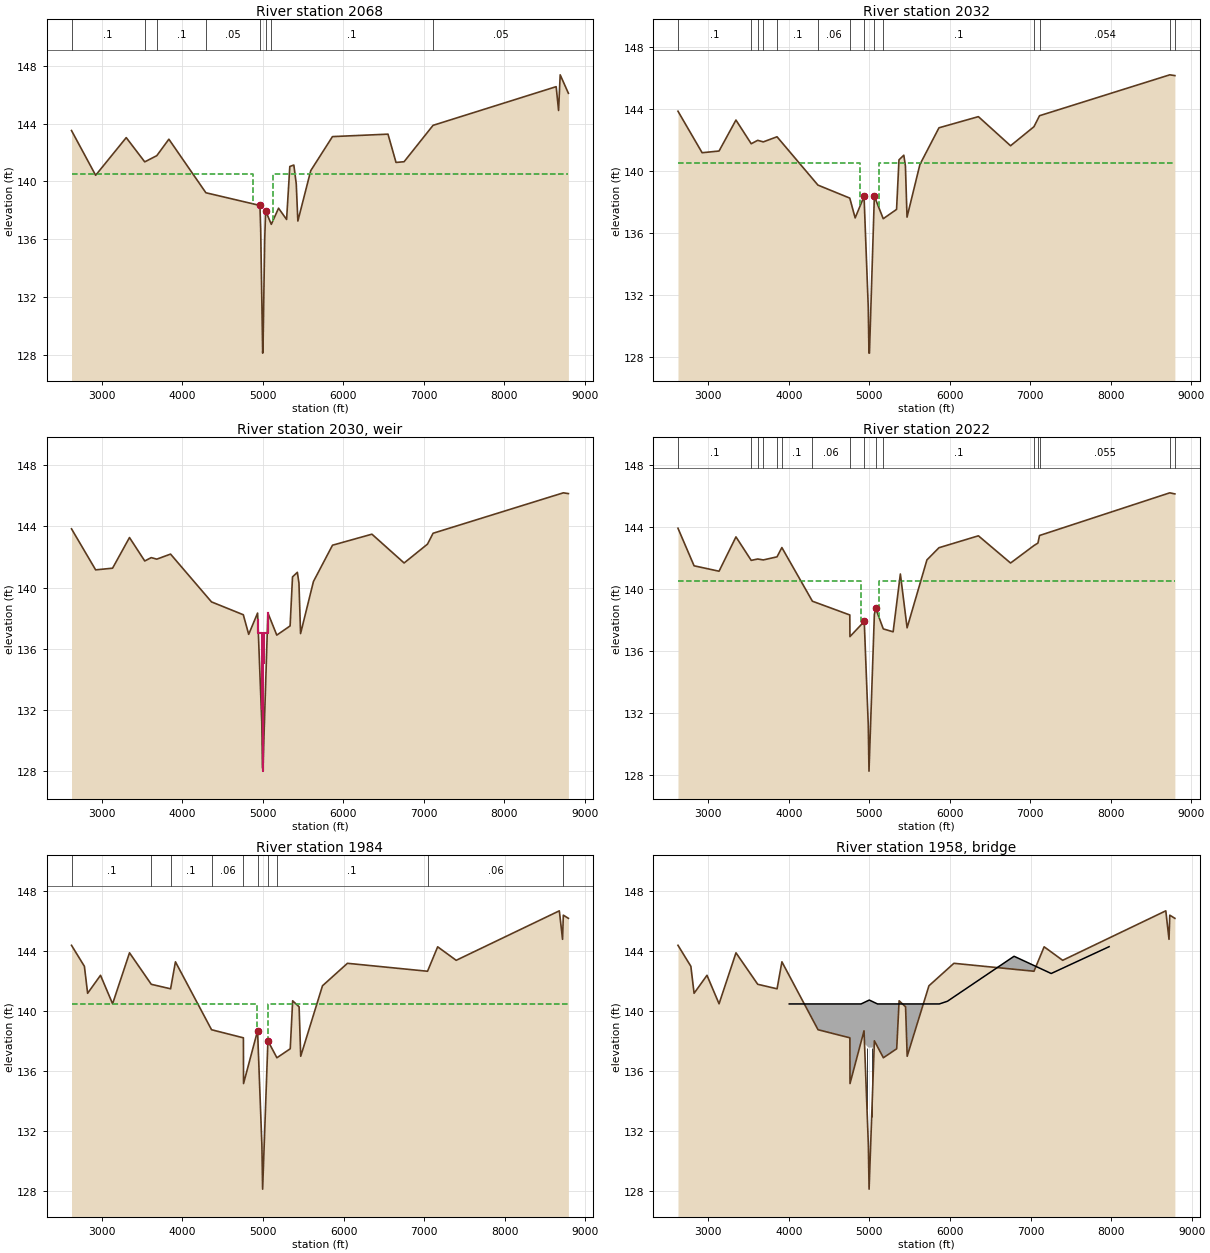
Type RM Length L Ch R = 1 ,2068    ,31.31,36,27.91
BEGIN DESCRIPTION:
S1_JARVIS-US - XS4
END DESCRIPTION:
XS GIS Cut Line= 5
       3022259.1      13915219.9      3021087.22     13913722.59
      3020670.47     13913619.11      3020574.69     13913560.87
      3017179.99     13915111.75
#Sta/Elev= 30
    2623  143.53    2923  140.43    3303  143.04    3533  141.36    3683  141.79
    3833  142.93    4293  139.22 4964.46  138.34 4973.75  136.75 4998.75  128.11
 5003.69  128.68 5023.67  135.94 5035.47  137.97  5105.9  137.03  5195.9  138.15
  5295.9  137.37  5335.9  141.04  5385.9  141.14  5415.9  139.84  5435.9  137.26
  5595.9  140.75  5865.9  143.11  6555.9  143.28  6655.9  141.32  6755.9  141.37
  7115.9  143.89  8645.9  146.57  8675.9  144.92  8695.9  147.39  8798.1  146.11
#Mann= 8 ,-1 , 0
    2623      .1       0    3533     .05       0    3683      .1       0
    4293     .05       0 4964.46    .015       0 5035.47     .05       0
  5105.9      .1       0  7115.9     .05       0
#XS Ineff= 2 , 0
       0 4875.46  140.49 5124.47       0  140.49
Permanent Ineff=
       F       F
Bank Sta=4964.46,5035.47
XS Rating Curve= 0
Exp/Cntr=.5,.3

Type RM Length L Ch R = 1 ,2032    ,8.7,10,7.75
BEGIN DESCRIPTION:
Interpolated Section Jan 2009
END DESCRIPTION:
XS GIS Cut Line= 6
      3022279.96     13915177.15      3021108.85     13913680.77
      3020705.58     13913569.77      3020588.66     13913565.67
      3020568.87     13913554.42      3017201.37     13915091.39
#Sta/Elev= 30
 2623.22  143.84 2923.17  141.16 3133.36  141.27 3343.42  143.27 3533.07  141.74
  3613.5  141.96 3683.04  141.86 3853.57  142.19 4361.82  139.07  4757.2  138.23
  4824.2  136.95  4934.6  138.34  4986.6  131.22  4995.7  128.22  5001.7  128.22
  5062.5  138.35 5172.99   136.9  5338.5   137.5  5368.5   140.7  5428.5     141
  5448.5   140.3  5468.5     137  5628.5   140.4 5865.25  142.77 6354.94  143.49
 6754.69  141.61 7045.07  142.84 7114.47  143.55 8732.35  146.19 8795.62  146.14
#Mann= 14 ,-1 , 0
 2623.22      .1       0 3533.07    .068       0  3613.5    .086       0
 3683.04    .086       0 3853.57      .1       0 4361.82     .06       0
  4757.2     .07       0  4934.6    .015       0  5062.5     .06       0
 5172.99      .1       0 7045.07    .086       0 7114.47    .054       0
 8732.35    .395       0 8795.62    .388       0
#XS Ineff= 2 , 0
       0  4881.6  140.49  5115.5       0  140.49
Permanent Ineff=
       F       F
Bank Sta=4934.6,5062.5
XS Rating Curve= 0
Exp/Cntr=.7,.5

Type RM Length L Ch R = 5 ,2030    ,,,
BEGIN DESCRIPTION:
Proposed Sheet pile Weir Upstream of Jarvis
END DESCRIPTION:
IW Pilot Flow=0
#Inline Weir SE= 19
  4936.9   137.9  4936.9  137.06  4966.7  137.06  4985.7  137.06  4985.7  135.06
  4990.7  135.06  4990.7  132.06  4995.7  132.06  4995.7  128.02  4998.7  128.02
  5001.7  128.02  5001.7  132.06  5006.7  132.06  5006.7  135.06  5011.7  135.06
  5011.7  137.06  5030.7  137.06  5062.5  137.06  5062.5  138.35
IW Dist,WD,Coef,Skew,MaxSub,Min_El,Is_Ogee,SpillHt,DesHd
4,1,2.6,0,.95,, 0 ,,,0,0,

Type RM Length L Ch R = 1 ,2022    ,33.04,38,29.46
BEGIN DESCRIPTION:
Interpolated Section Jan 2009
END DESCRIPTION:
XS GIS Cut Line= 6
      3022283.97     13915168.93      3021112.02     13913671.67
      3020708.53     13913559.87       3020591.4     13913555.76
       3020571.8     13913547.04      3017205.48     13915087.47
#Sta/Elev= 30
 2623.28  143.93 2823.32   141.5  3133.4  141.15 3343.45  143.37 3533.09  141.85
 3613.52  141.94 3683.05  141.88 3853.57  142.08 3913.59  142.68 4292.92  139.21
 4757.39  138.32 4759.09  136.92  4936.9   137.9  4986.6  131.22  4995.7  128.22
  5062.5  138.35  5078.5  138.75 5173.32  137.42 5295.52  137.23 5385.45  140.97
 5469.11  137.49 5715.18  141.88 5865.07  142.67 6354.67  143.44 6754.35  141.68
 7044.68  142.81 7094.08  142.97 7114.07  143.46 8731.67  146.22 8794.93  146.15
#Mann= 16 ,-1 , 0
 2623.28      .1       0 3533.09    .073       0 3613.52    .094       0
 3683.05    .082       0 3853.57    .072       0 3913.59      .1       0
 4292.92     .06       0 4757.39     .07       0  4936.9    .015       0
  5078.5     .06       0 5173.32      .1       0 7044.68    .088       0
 7094.08    .094       0 7114.07    .055       0 8731.67    .488       0
 8794.93    .482       0
#XS Ineff= 2 , 0
       0  4893.9  140.49  5121.5       0  140.49
Permanent Ineff=
       F       F
Bank Sta=4936.9,5078.5
XS Rating Curve= 0
Exp/Cntr=.7,.5

Type RM Length L Ch R = 1 ,1984    ,86,88,97
BEGIN DESCRIPTION:
S1_JARVIS-US - XS3
END DESCRIPTION:
XS GIS Cut Line= 5
      3022299.22     13915137.69      3021127.35      13913640.3
       3020727.3     13913526.96      3020610.33     13913522.85
       3017221.1     13915072.59
#Sta/Elev= 30
  2623.6   144.4  2783.6     143  2823.6   141.2  2983.6   142.4  3133.6   140.5
  3343.6   143.9  3613.6   141.8  3853.6   141.5  3913.6   143.3  4361.7  138.77
  4757.2  138.23  4758.9  135.18    4933   138.7  4986.5  131.11  4995.7  128.14
  5061.4  138.03 5172.99   136.9  5338.5   137.5  5368.5   140.7  5448.5   140.3
  5468.5     137  5738.5   141.7  6048.5   143.2  7042.6  142.67  7168.5   144.3
  7398.5   143.4  8678.5   146.7  8718.5   144.8    8728  146.41  8791.2   146.2
#Mann= 10 ,-1 , 0
  2623.6      .1       0  3613.6     .06       0  3853.6      .1       0
  4361.7     .06       0  4757.2     .07       0    4933    .015       0
  5061.4     .06       0 5172.99      .1       0  7042.6     .06       0
    8728     .99       0
#XS Ineff= 2 , 0
       0    4928  140.49  5066.4       0  140.49
Permanent Ineff=
       F       F
Bank Sta=4933,5061.4
XS Rating Curve= 0
Exp/Cntr=.5,.3

Type RM Length L Ch R = 3 ,1958    ,,,
BEGIN DESCRIPTION:
JARVIS (12-2008)
Structure ID: K145-00-00-S1
END DESCRIPTION:
Bridge Culvert--1,0,-1,-1, 0
Deck Dist Width WeirC Skew NumUp NumDn MinLoCord MaxHiCord MaxSubmerge Is_Ogee
5,78,2.6,0, 13, 13, , , .95, 0, ,,,
    4005    4896    4939    4939    4998    5057    5057    5100    5868    5968
    6795    7256    7975
  140.49  140.49   140.6   140.6  140.75   140.6   140.6  140.49  140.49  140.67
  143.67  142.52  144.31
     100     100     100  137.58  137.58  137.58     100     100     100     100
     100     100     100
    4005    4896    4939    4939    4998    5057    5057    5100    5868    5968
    6795    7256    7975
  140.49  140.49   140.6   140.6  140.75   140.6   140.6  140.49  140.49  140.67
  143.67  142.52  144.31
     100     100     100  137.58  137.58  137.58     100     100     100     100
     100     100     100
Pier Skew, UpSta & Num, DnSta & Num=  ,4969.7, 2 ,4969.7, 2 , 0 , 0 , 0 ,,
       2       2
       0  137.83
    1.66    1.66
       0  137.83
Pier Skew, UpSta & Num, DnSta & Num=  ,5027.7, 2 ,5027.7, 2 , 0 , 0 , 0 ,,
       2       2
       0  137.83
    1.66    1.66
       0  137.83
BR Coef= 1 , 1 , 0 ,1.25, 0 ,,,.8,0,2,0,
WSPro=,,,, 1 ,,,, 0 ,,,, 0 ,,,,-1 ,-1 ,-1 , 0 , 0 , 0 , 0 , 0
BC Design=,, 0 ,, 0 ,,,,,,
BC HTab HWMax=147.5

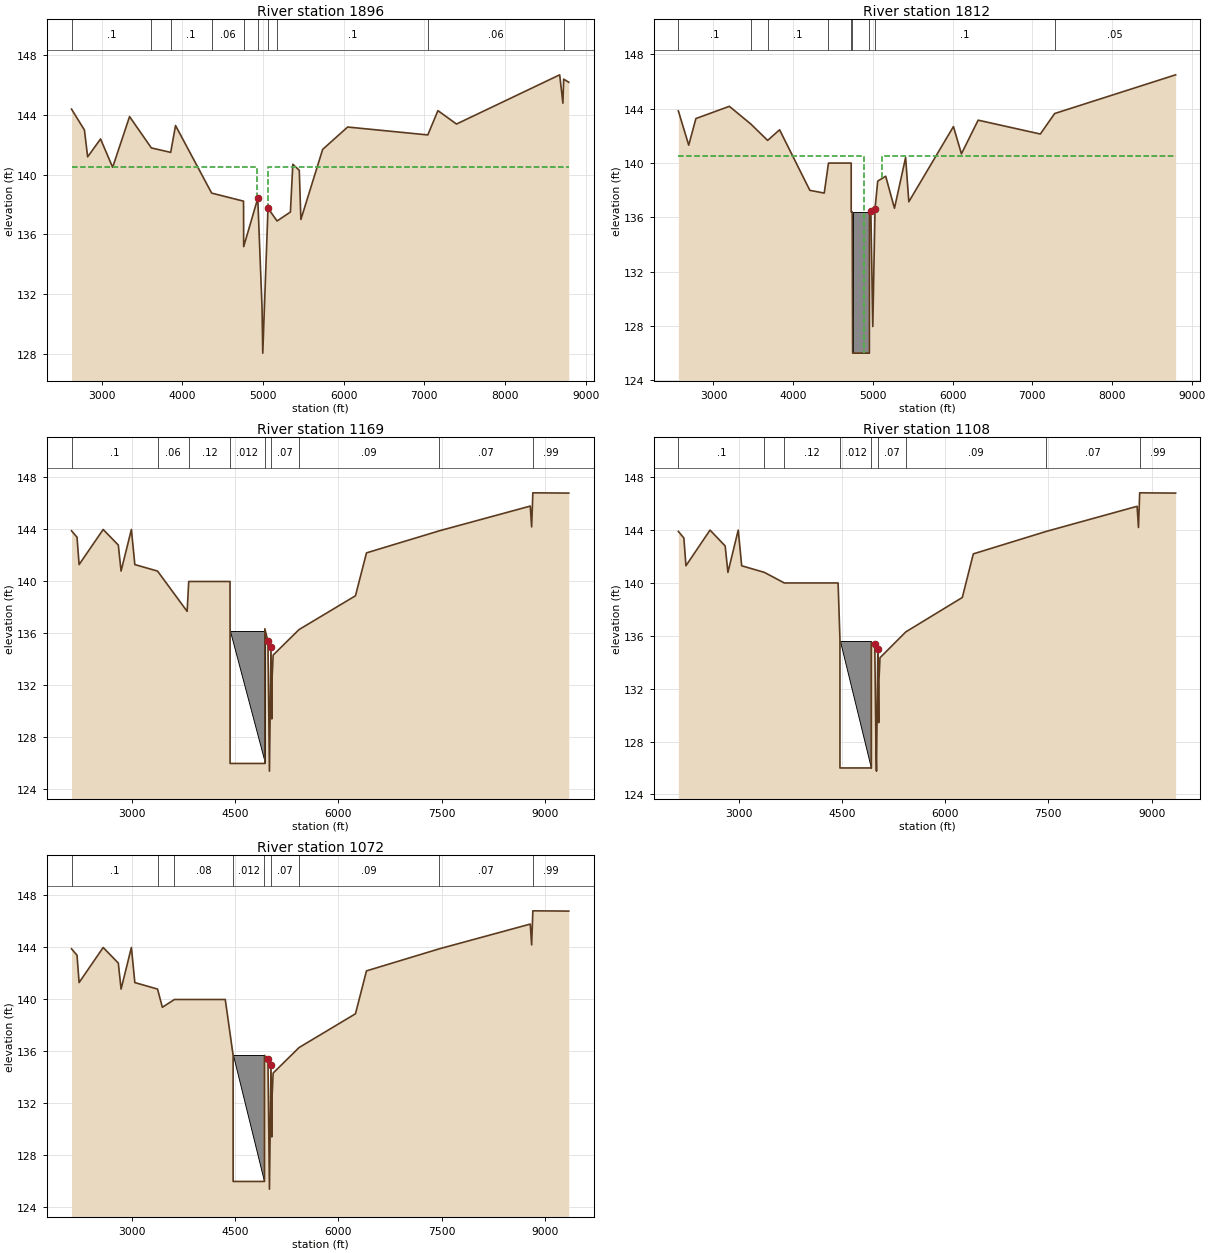
Type RM Length L Ch R = 1 ,1896    ,53.58,84,67.71
BEGIN DESCRIPTION:
S1_JARVIS-DS - XS2
END DESCRIPTION:
XS GIS Cut Line= 5
        3022315.      13915090.4      3021106.07     13913546.44
      3020730.36     13913440.02       3020614.1     13913435.93
      3017212.77     13915019.47
#Sta/Elev= 30
  2623.6   144.4  2783.6     143  2823.6   141.2  2983.6   142.4  3133.6   140.5
  3343.6   143.9  3613.6   141.8  3853.6   141.5  3913.6   143.3  4361.7  138.77
  4757.2  138.23  4758.9  135.18  4933.8  138.42  4986.5  131.11  4995.7  128.04
  5060.6  137.76 5172.99   136.9  5338.5   137.5  5368.5   140.7  5448.5   140.3
  5468.5     137  5738.5   141.7  6048.5   143.2  7042.6  142.67  7168.5   144.3
  7398.5   143.4  8678.5   146.7  8718.5   144.8    8728  146.41  8791.2   146.2
#Mann= 10 ,-1 , 0
  2623.6      .1       0  3613.6     .06       0  3853.6      .1       0
  4361.7     .06       0  4757.2     .07       0  4933.8    .015       0
  5060.6     .06       0 5172.99      .1       0  7042.6     .06       0
    8728     .99       0
#XS Ineff= 2 , 0
       0  4928.8  140.49  5065.6       0  140.49
Permanent Ineff=
       F       F
Bank Sta=4933.8,5060.6
XS Rating Curve= 0
Exp/Cntr=.5,.3

Type RM Length L Ch R = 1 ,1812    ,447.42,643,538.29
BEGIN DESCRIPTION:
S1_JARVIS-DS - XS1
IFA DUE TO BRIDGE
END DESCRIPTION:
XS GIS Cut Line= 5
      3022291.37      13915049.2      3021121.07     13913487.74
      3020687.38     13913356.84      3020610.63     13913354.44
      3017194.65     13914919.16
#Sta/Elev= 30
  2559.7  143.84  2689.7  141.32  2779.7  143.28  3199.7  144.18  3469.7  142.87
  3679.7  141.67  3829.7  142.45  4209.7  137.99  4389.7  137.79  4443.1     140
  4728.1     140  4728.1   136.4  4741.1   136.4  4746.1     126  4956.1     126
  4956.1   136.4  4974.8  136.45 4998.86  127.96 5027.18  136.65  5060.9  138.67
  5160.9  139.03  5270.9  136.67  5410.9  140.41  5450.9  137.15  6010.9  142.69
  6110.9  140.68  6320.9  143.16  7100.9  142.14  7280.9  143.65  8798.2   146.5
#Mann= 9 ,-1 , 0
  2559.7      .1       0  3469.7     .05       0  3679.7      .1       0
  4443.1     .12       0  4728.1     .08       0  4741.1    .012       0
  4956.1     .08       0 5027.18      .1       0  7280.9     .05       0
#XS Ineff= 2 , 0
       0  4885.8  140.49 5116.18       0  140.49
Permanent Ineff=
       F       F
#Block Obstruct= 1 ,-1
  4746.1  4956.1   136.4
Bank Sta=4974.8,5027.18
XS Rating Curve= 0
Exp/Cntr=.3,.1

Type RM Length L Ch R = 1 ,1169    ,61,61,61
BEGIN DESCRIPTION:
Cross Section K145-00-00-X01A
END DESCRIPTION:
XS GIS Cut Line= 5
      3022299.22     13915046.55       3021283.6     13913119.46
      3020660.58      13912847.6      3020542.58      13912847.6
      3016830.47     13914916.34
#Sta/Elev= 30
  2123.7   143.9  2203.7   143.4  2233.7   141.3  2583.7     144  2803.7   142.8
  2843.7   140.8  2993.7     144  3043.7   141.3  3373.7   140.8  3803.7   137.7
  3826.8     140  4426.8     140  4427.8   136.2  4427.8     126  4932.8     126
  4932.8  136.36  4977.8   135.4  4999.9  125.41    5022  134.97  5034.3  129.43
  5038.7  132.64  5053.7  134.34  5429.8   136.3  6249.8   138.9  6409.8   142.2
  7469.8   143.9  8789.8   145.8  8809.8   144.2  8827.5  146.82  9349.4   146.8
#Mann= 9 ,-1 , 0
  2123.7      .1       0  3373.7     .06       0  3826.8     .12       0
  4427.8    .012       0  4932.8     .08       0    5022     .07       0
  5429.8     .09       0  7469.8     .07       0  8827.5     .99       0
#Block Obstruct= 1 ,-1
  4427.8  4932.8   136.2
Bank Sta=4977.8,5022
XS Rating Curve= 0
Exp/Cntr=.3,.1

Type RM Length L Ch R = 1 ,1108    ,36,36,36
BEGIN DESCRIPTION:
copied xs 1169
END DESCRIPTION:
XS GIS Cut Line= 5
      3022318.54      13914984.4      3021302.92      13913057.3
       3020679.9      13912785.4       3020561.9      13912785.4
      3016849.79      13914854.2
#Sta/Elev= 30
  2123.7   143.9  2203.7   143.4  2233.7   141.3  2583.7     144  2803.7   142.8
  2843.7   140.8  2993.7     144  3043.7   141.3  3373.7   140.8  3662.8     140
  4444.8     140    4472   135.7    4472     126  4927.8     126  4927.8   135.5
  4977.8   135.4  4996.4  126.94  5002.6  125.76    5022  134.97  5034.3  129.43
  5038.7  132.64  5053.7  134.34  5429.8   136.3  6249.8   138.9  6409.8   142.2
  7469.8   143.9  8789.8   145.8  8809.8   144.2  8827.5  146.82  9349.4   146.8
#Mann= 9 ,-1 , 0
  2123.7      .1       0  3373.7     .06       0  3662.8     .12       0
    4472    .012       0  4927.8     .08       0    5022     .07       0
  5429.8     .09       0  7469.8     .07       0  8827.5     .99       0
#Block Obstruct= 1 ,-1
    4472  4927.8   135.6
Bank Sta=4977.8,5022
XS Rating Curve= 0
Exp/Cntr=.3,.1

Type RM Length L Ch R = 1 ,1072    ,1072,1072,1072
BEGIN DESCRIPTION:
copied xs 1169
NO FILL
END DESCRIPTION:
XS GIS Cut Line= 5
      3022323.49      13914949.7      3021307.87      13913022.6
      3020684.85      13912750.8      3020566.85      13912750.8
      3016854.74      13914819.5
#Sta/Elev= 30
  2123.7   143.9  2203.7   143.4  2233.7   141.3  2583.7     144  2803.7   142.8
  2843.7   140.8  2993.7     144  3043.7   141.3  3373.7   140.8  3443.7   139.4
  3619.8     140  4357.8     140    4472   135.7    4472     126  4927.8     126
  4927.8   135.7  4977.8   135.4  4999.9  125.41    5022  134.97  5034.3  129.43
  5038.7  132.64  5053.7  134.34  5429.8   136.3  6249.8   138.9  6409.8   142.2
  7469.8   143.9  8789.8   145.8  8809.8   144.2  8827.5  146.82  9349.4   146.8
#Mann= 9 ,-1 , 0
  2123.7      .1       0  3373.7     .06       0  3619.8     .08       0
    4472    .012       0  4927.8     .08       0    5022     .07       0
  5429.8     .09       0  7469.8     .07       0  8827.5     .99       0
#Block Obstruct= 1 ,-1
    4472  4927.8   135.7
Bank Sta=4977.8,5022
XS Rating Curve= 0
Exp/Cntr=.3,.1

Chan Stop Cuts=-1